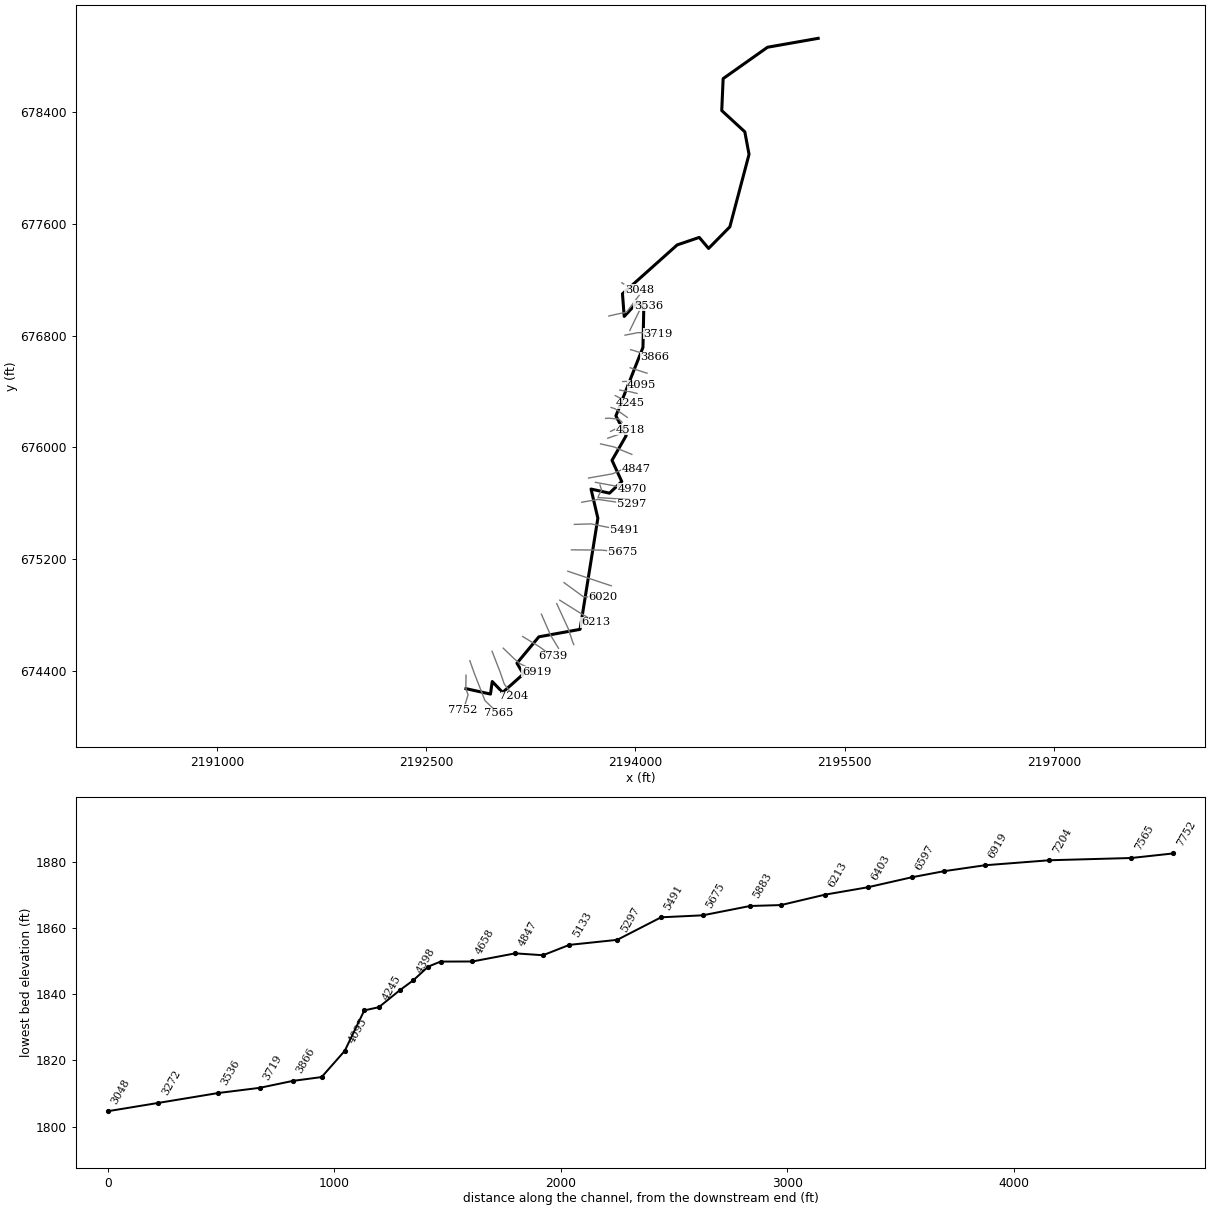
--- INDIANCPRN.prj (project) ---

Proj Title=INDIANCPRN
Current Plan=p01
Default Exp/Contr=0,0
English Units
Geom File=g01
Flow File=f01
Plan File=p01
BEGIN DESCRIPTION:
-------- MODELED AS PART OF WVEMD CTP PROGRAM, 2023----------
Stream Name: Indian Camp Run
Flood Zone:  AFH
Upshur County, WV
HEC-RAS Version: RAS 6.3
Vertical Datum: NAVD88
Projection: NAD 1983 StatePlane West Virginia S FIPS 4702 (US Feet)
Terrain: 1-meter LIDAR (FEMA Region III 3DEP collected 2016-2018)
Land Use: 2019 NLCD
Hydrologic Method:
WV SIR2010-5033 regression equations
Additional Model Notes:
None
END DESCRIPTION:
DSS Export Rating Curves= 0
DSS Export Rating Curve Sorted= 0
DSS Export Volume Flow Curves= 0
DXF OffsetX= 0
DXF OffsetY= 0
DXF ScaleX= 0
DXF ScaleY= 0

--- INDIANCPRN.p01 (plan) ---

Plan Title=Floodplain
Program Version=4.00
Geom File=g01
Flow File=f01
K Sum by GR=0
Std Step Tol=0.01
Critical Tol=0.01
Num of Std Step Trials=20
Max Error Tol=0.3
Flow Tol Ratio=0.001
Split Flow NTrial=30
Split Flow Tol=0.02
Split Flow Ratio=0.02
Log Output Level=0
Friction Slope Method=1
Unsteady Friction Slope Method=2
Unsteady Bridges Friction Slope Method=1
Global Log Level=0
CheckData=False
Run HTab=0
Run UNet=0
Run PostProcess=0
UNET Theta=0
UNET Theta Warmup=0
UNET ZTol=0
UNET ZSATol=0
UNET MxIter=0
UNET MaxInSteps=0
UNET DtIC=0
UNET DtMin=0
UNET MaxCRTS=0
UNET WFStab=0
UNET SFStab=0
UNET WFX=0
UNET SFX=0
UNET DSS MLevel=0
UNET DZMax Abort=0
UNET Convert EG Bridges=0
UNET Use Existing IB Tables=0
UNET Froude Limit=0
UNET Froude Power=0
Write IC File=0
Echo Input=False
Echo Output=False
Write Detailed=0

--- INDIANCPRN.f01 (steady flow) ---

Flow Title=Flows
Program Version=6.30
Number of Profiles= 1
Profile Names=01pct
River Rch & RM=INDIANCPRN,Main            ,7752
     311
River Rch & RM=INDIANCPRN,Main            ,6919
     346
River Rch & RM=INDIANCPRN,Main            ,3272
     417
Boundary for River Rch & Prof#=INDIANCPRN,Main            , 1
Up Type= 0
Dn Type= 3
Dn Slope=0.03266
DSS Import GetInterval= 0
DSS Import GetPeak= 0
DSS Import FillOption= 0

--- INDIANCPRN.g01 (geometry) ---

Geom Title=Geometry
Program Version=6.30

River Reach=INDIANCPRN      ,Main
Reach XY= 30
      2192785.23      674270.056     2192961.192      674231.195
     2192973.583      674321.222       2193048.3      674242.756
     2193196.533      674374.878     2193150.718      674452.514
     2193307.736      674641.497     2193602.857      674694.866
     2193730.543       675491.49     2193681.466      675700.446
     2193813.874        675670.8     2193901.813      675754.274
     2193831.903      675906.227     2193933.462      676083.162
     2193859.775      676224.813     2194053.708      676715.527
     2194059.546      676996.254     2194016.078      677041.382
     2193919.269      676937.418     2193906.964      677099.473
     2194299.008      677449.852     2194457.028      677503.565
     2194523.961      677424.555     2194676.315      677579.341
     2194813.874        678098.7     2194783.598       678260.24
      2194618.31      678412.565     2194628.297      678641.496
     2194946.282      678866.306     2195309.338      678930.149

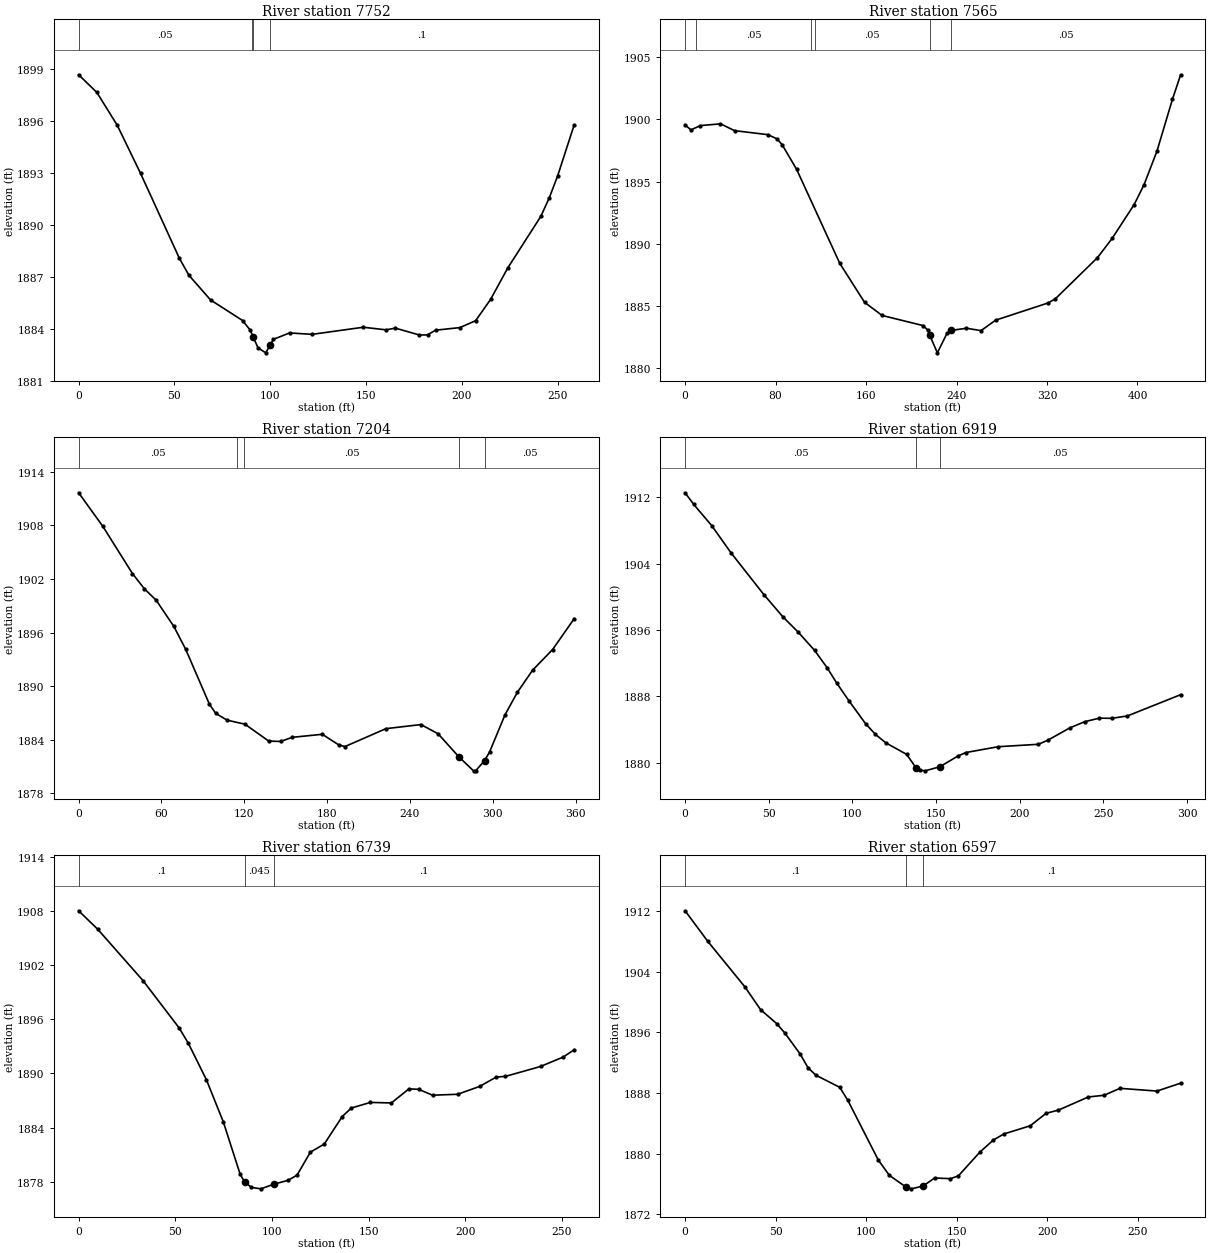
Type RM Length L Ch R = 1 ,7752    ,177.9,186.5,185
XS GIS Cut Line= 6
2192785.86252485674366.6951450722192784.78443819674287.163314628
2192786.50944597 674262.710495382192800.68204866674226.522664203
2192775.42374925674143.859138864 2192763.3955564674117.329629994
#Sta/Elev= 30
       0 1898.68     9.5 1897.66    20.1 1895.77    32.3 1892.98    52.5 1888.08
    57.5 1887.09    68.8 1885.66    85.5 1884.47    89.6  1883.9    91.11883.497
    93.6 1882.89    97.6  1882.6     1001883.068   101.6 1883.38     110 1883.75
   121.8 1883.67   148.5 1884.08   160.4 1883.93   165.2 1884.03   177.8 1883.63
     182 1883.64   186.2 1883.91   198.9 1884.06   207.1 1884.46   214.9 1885.69
   223.8  1887.5   241.1 1890.49   245.5 1891.56   249.9 1892.84   258.5 1895.78
#Mann= 4 ,-1,0
       0     .05       0    90.3    .045       0    91.1    .045       0
     100      .1       0
Bank Sta=91.1,100
XS Rating Curve= 0 ,0
Exp/Cntr=0.3,0.1

Type RM Length L Ch R = 1 ,7565    ,312.8,360.8,343.8
XS GIS Cut Line= 4
2192813.02738443674469.995449508 2192845.7740293674378.530682786
2192921.43007091674184.3092028342193017.41161624674092.844436113
#Sta/Elev= 30
       0 1899.57     5.1 1899.16    13.6 1899.51    31.3 1899.65    43.8  1899.1
    73.1 1898.78    81.3 1898.44    85.8 1897.97    98.6 1895.99   136.8 1888.41
   158.7 1885.28   174.2 1884.22   210.2 1883.41   214.5 1883.06   216.21882.646
   223.1 1881.21   231.7  1882.8   235.31883.018   248.8 1883.19   261.7    1883
   274.6 1883.84   321.1 1885.23   327.5 1885.57   364.6 1888.87   377.6 1890.42
   397.1 1893.15   405.9 1894.76   417.3 1897.46   430.9 1901.61   438.2  1903.6
#Mann= 6 ,-1,0
       0     .06       0      10     .05       0   110.9    .045       0
     115     .05       0   216.2     .05       0   235.3     .05       0
Bank Sta=216.2,235.3
XS Rating Curve= 0 ,0
Exp/Cntr=0.3,0.1

Type RM Length L Ch R = 1 ,7204    ,273.8,285.4,283.9
XS GIS Cut Line= 4
2192972.54306678674537.5325815772193030.98905272674386.890110787
2193059.80045424674302.9254549362193125.65508628674216.491250385
#Sta/Elev= 30
       0 1911.65    17.5  1907.9      39 1902.61    47.6 1900.91    56.2 1899.62
      69 1896.69    77.6 1894.12    94.8 1887.97    99.4 1886.95   107.6  1886.2
   120.5 1885.75   137.7 1883.86   146.3 1883.82   154.8 1884.28   176.5 1884.62
   188.8  1883.4     193 1883.25   222.6 1885.25     248 1885.71   260.4 1884.68
   275.71882.062   286.1 1880.53   287.7 1880.55   294.11881.674   297.8 1882.67
   308.9  1886.8   317.9 1889.33   328.9  1891.8   343.4 1894.11     359 1897.56
#Mann= 5 ,-1,0
       0     .05       0   114.4    .045       0   119.8     .05       0
   275.7     .05       0   294.1     .05       0
Bank Sta=275.7,294.1
XS Rating Curve= 0 ,0
Exp/Cntr=0.3,0.1

Type RM Length L Ch R = 1 ,6919    ,177.5,180.1,181.5
XS GIS Cut Line= 4
2193052.42638181674560.0309934312193132.83982663674482.618050285
2193173.04654904674448.4123312212193291.86641526674391.402799447
#Sta/Elev= 30
       0 1912.53     5.2 1911.12      16 1908.55    27.3 1905.33    47.1 1900.25
    58.4 1897.59    67.6 1895.73    77.4 1893.53    84.9 1891.44    90.6  1889.6
      98 1887.43   107.9 1884.69   113.8  1883.4     120 1882.38   132.4    1881
   137.91879.407   140.5 1879.08   143.4 1879.01   152.21879.497   163.2 1880.81
   167.9 1881.22   187.2 1881.92   211.2 1882.21   216.7 1882.69     230 1884.19
   238.9 1884.94   247.7 1885.36   255.1 1885.34   264.4 1885.63   296.2 1888.19
#Mann= 3 ,-1,0
       0     .05       0   137.9    .045       0   152.2     .05       0
Bank Sta=137.9,152.2
XS Rating Curve= 0 ,0
Exp/Cntr(USF)=0,0
Exp/Cntr=0.3,0.1

Type RM Length L Ch R = 1 ,6739    ,148.5,142,134.8
XS GIS Cut Line= 3
2193191.73755705674643.6554918132193313.55792494 674569.24305034
2193404.77317578674501.431712546
#Sta/Elev= 30
       0 1908.01     9.9 1905.96    33.3 1900.28    52.1 1895.01    56.8 1893.32
    66.1 1889.31    74.9 1884.61    83.6 1878.82    85.9 1877.98    89.4 1877.38
    94.3 1877.22   100.91877.727   108.3 1878.16     113 1878.73   119.9 1881.28
   127.1 1882.18   136.4 1885.23   141.1 1886.17     151 1886.79   161.8 1886.73
   170.9 1888.29   175.9 1888.24   183.1 1887.59   196.1 1887.69   207.6 1888.57
   216.1  1889.6   220.8 1889.67     239 1890.77   250.7 1891.81   256.4 1892.62
#Mann= 3 ,-1,0
       0      .1       0    85.9    .045       0   100.9      .1       0
Bank Sta=85.9,100.9
XS Rating Curve= 0 ,0
Exp/Cntr(USF)=0,0
Exp/Cntr=0.3,0.1

Type RM Length L Ch R = 1 ,6597    ,190.2,194.1,191.8
XS GIS Cut Line= 3
2193325.93923486674803.4376438582193391.07412516674654.210693689
2193448.43171513674559.424845861
#Sta/Elev= 30
       0 1912.01    12.5 1907.99      33 1901.99    41.7 1898.98    50.5 1897.16
    55.1  1895.9    63.6 1893.11    67.9 1891.32    72.3 1890.34    85.4 1888.75
    89.8 1887.06   106.7 1879.16   112.8 1877.15   122.11875.595   124.9 1875.38
   131.31875.741   137.8 1876.81   146.5 1876.72   150.9 1877.09   162.8 1880.23
   170.2 1881.81     176 1882.61   190.6 1883.69   199.3 1885.33   206.1 1885.75
   222.6 1887.48   231.4 1887.71   240.1 1888.62   260.5 1888.26   273.6  1889.3
#Mann= 3 ,-1,0
       0      .1       0   122.1    .045       0   131.3      .1       0
Bank Sta=122.1,131.3
XS Rating Curve= 0 ,0
Exp/Cntr(USF)=0,0
Exp/Cntr=0.3,0.1

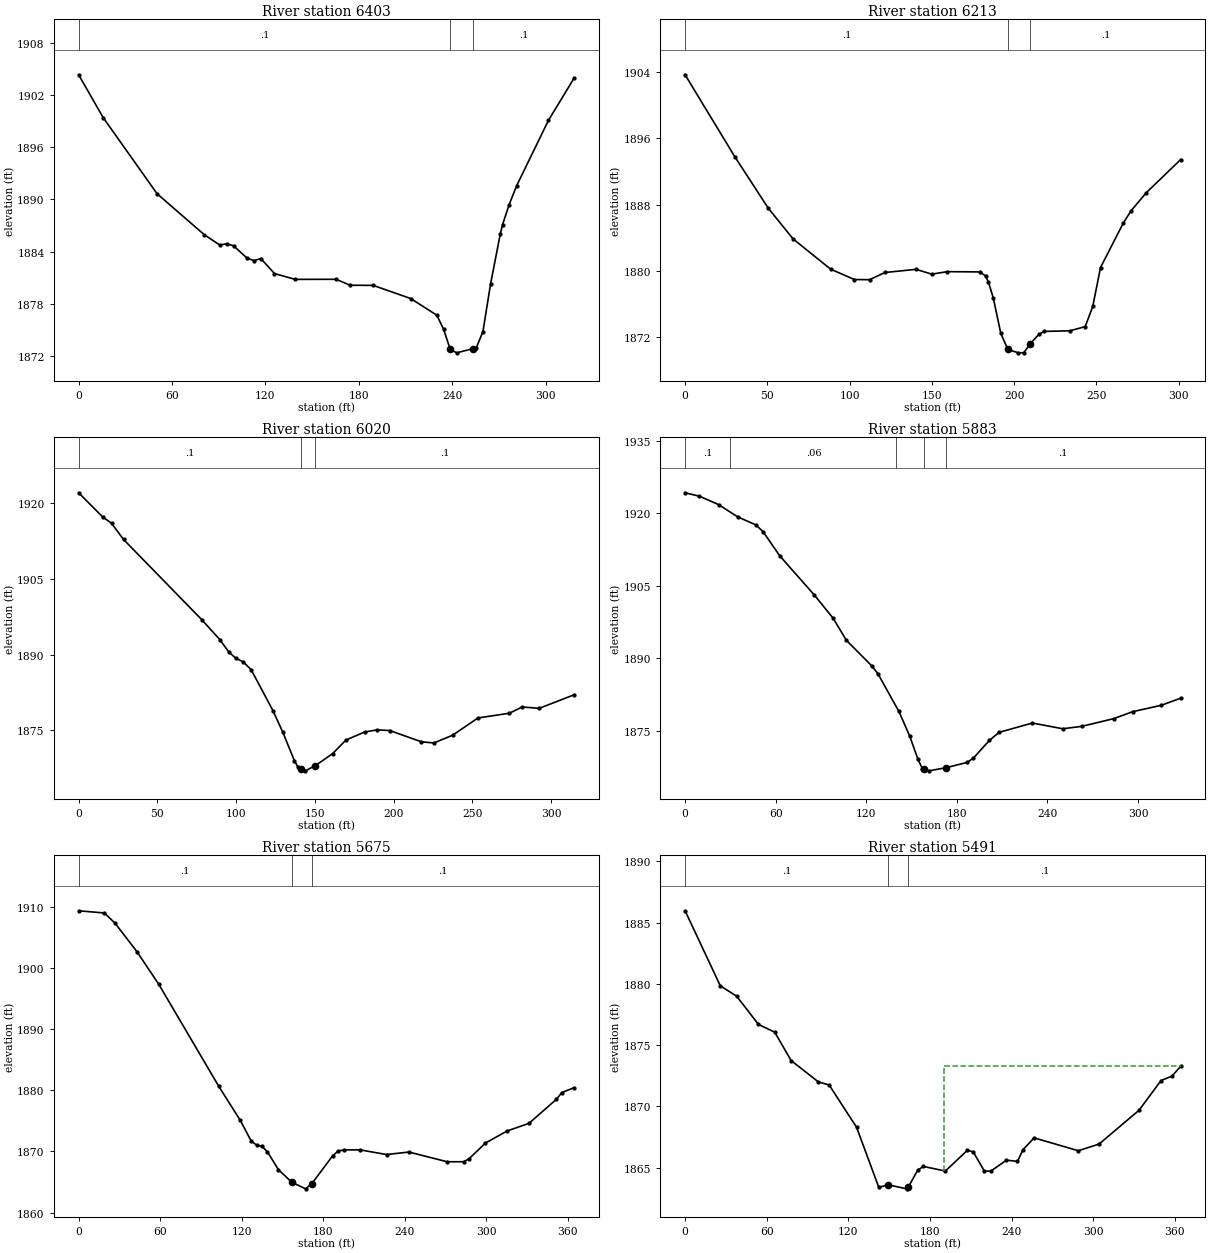
Type RM Length L Ch R = 1 ,6403    ,180.1,189.2,197.3
XS GIS Cut Line= 4
2193435.66558068674879.5617048412193518.42741814674699.416251883
2193551.83900443674599.5788927962193557.67197968 674585.96861721
#Sta/Elev= 30
       0 1904.31    15.8 1899.38    50.4 1890.64    80.6 1885.95    90.7 1884.74
    95.1  1884.9    99.5 1884.66   108.3 1883.22   112.7 1882.96   117.1 1883.19
   125.8 1881.47   139.1  1880.8   165.5 1880.81   174.3 1880.13   189.2 1880.11
   213.3  1878.6   230.1 1876.68   234.4 1875.08   238.71872.759   242.8 1872.36
     2531872.826   255.4 1872.93   259.7  1874.8   264.6 1880.28   270.9 1886.07
   272.3 1887.09   276.5 1889.37   281.4 1891.58   301.8 1899.08   318.3 1903.94
#Mann= 3 ,-1,0
       0      .1       0   238.7    .045       0     253      .1       0
Bank Sta=238.7,253
XS Rating Curve= 0 ,0
Exp/Cntr(USF)=0,0
Exp/Cntr=0.3,0.1

Type RM Length L Ch R = 1 ,6213    ,190.5,193.7,192.7
XS GIS Cut Line= 3
2193457.15135409674903.9672009842193595.17443101674817.552752821
2193713.99429724674746.740913355
#Sta/Elev= 30
       0 1903.69    30.3 1893.77    50.5  1887.6    65.6 1883.88    88.4 1880.23
   102.9 1878.97   112.1 1878.95   121.5 1879.82   140.4  1880.2   149.9 1879.62
   159.3 1879.92   179.2 1879.89   182.6  1879.4   184.3 1878.71   187.3 1876.76
   191.9 1872.46   196.21870.524   202.6 1870.12   205.9 1870.14   209.9 1871.24
   215.2 1872.39   218.3 1872.71   233.9 1872.78   243.2 1873.29   247.8 1875.73
   252.5 1880.42   266.4 1885.81   271.1 1887.28   280.4 1889.47   301.2 1893.45
#Mann= 3 ,-1,0
       0      .1       0   196.2    .045       0   209.9      .1       0
Bank Sta=196.2,209.9
XS Rating Curve= 0 ,0
Exp/Cntr(USF)=0,0
Exp/Cntr=0.3,0.1

Type RM Length L Ch R = 1 ,6020    ,132.6,136.6,139.5
XS GIS Cut Line= 3
2193487.79487009675030.0070015782193626.48472516674928.656722869
2193769.17524913674923.322497674
#Sta/Elev= 30
       0 1922.09    15.2 1917.32    20.9 1916.04    28.5 1912.84    78.2 1896.93
    89.6    1893    95.3 1890.55    99.6 1889.34   104.5 1888.57   109.5 1887.04
   123.4 1878.89   129.7 1874.58     137 1868.97   139.2 1867.76   141.1 1867.32
     144 1866.98   150.31868.017   161.2 1870.38   169.7 1873.08   181.5 1874.67
   189.5  1875.1   197.5 1874.97   217.5 1872.75   225.5  1872.5   237.5 1874.05
   253.5 1877.46   273.5  1878.4   281.5 1879.63   292.5 1879.38   314.6 1882.06
#Mann= 3 ,-1,0
       0      .1       0   141.1    .045       0   150.3      .1       0
Bank Sta=141.1,150.3
XS Rating Curve= 0 ,0
Exp/Cntr(USF)=0,0
Exp/Cntr=0.3,0.1

Type RM Length L Ch R = 1 ,5883    ,204.4,208.6,212.3
XS GIS Cut Line= 3
2193515.17027477675111.5377799852193712.98112575675044.859965046
2193826.33341115675007.075869913
#Sta/Elev= 30
       0 1924.26     9.5 1923.55    22.2 1921.81    34.8 1919.28    46.9 1917.61
    51.7 1916.19    62.6 1911.24    85.5 1903.13    98.1 1898.27   106.8 1893.73
   123.5 1888.47   127.7 1886.81   141.6    1879   148.8 1873.87   154.2 1869.09
   157.2 1867.11   157.91867.034   161.5  1866.7   172.71867.344   186.8 1868.44
     191 1869.35   201.5 1872.99   207.9 1874.66     230  1876.6   250.1 1875.41
   262.7 1875.91   283.8  1877.5   296.5 1878.95   315.4 1880.27   328.2 1881.74
#Mann= 5 ,-1,0
       0      .1       0      30     .06       0     140      .1       0
   157.9    .045       0   172.7      .1       0
Bank Sta=157.9,172.7
XS Rating Curve= 0 ,0
Exp/Cntr(USF)=0,0
Exp/Cntr=0.3,0.1

Type RM Length L Ch R = 1 ,5675    ,185.8,183.8,181
XS GIS Cut Line= 3
2193541.21770367675264.691323326 2193755.2452578675262.862027991
2193905.24747522675248.227665316
#Sta/Elev= 30
       0 1909.36      19    1909      27 1907.28      43 1902.64      59 1897.33
     103  1880.7     119 1875.07     127  1871.7     131 1871.02     135 1870.82
     139 1869.92     147 1867.03   156.71864.991     167 1863.88   171.61864.719
     187  1869.3     191 1870.05     195 1870.25     207 1870.26   226.6 1869.49
   243.1  1869.9   271.2 1868.31   283.3 1868.31   287.3 1868.79   299.4 1871.37
   315.4 1873.35   331.5  1874.6   351.6 1878.52   355.6 1879.63   364.7 1880.43
#Mann= 3 ,-1,0
       0      .1       0   156.7    .045       0   171.6      .1       0
Bank Sta=156.7,171.6
XS Rating Curve= 0 ,0
Exp/Cntr(USF)=0,0
Exp/Cntr=0.3,0.1

Type RM Length L Ch R = 1 ,5491    ,188,193.9,197.3
XS GIS Cut Line= 4
2193562.33070774675446.9504539042193682.35077463675450.654776956
2193791.25787237675428.4288386432193922.39090841675406.202900329
#Sta/Elev= 30
       0 1885.97    25.9 1879.84    37.9    1879    53.9  1876.7    65.9 1876.06
    77.9 1873.75    97.9 1872.01   105.9 1871.75     126 1868.31   142.4 1863.39
   149.11863.617   162.8 1863.28     1641863.414   170.9 1864.79     175 1865.11
   191.3 1864.73   207.5 1866.43   211.8 1866.29   219.9 1864.74   224.6 1864.72
   236.2 1865.62   244.3 1865.52   248.4 1866.48   256.5 1867.44     289 1866.39
   304.2 1866.93   333.6 1869.69   349.8 1872.12   357.9 1872.48   364.2 1873.28
#Mann= 3 ,-1,0
       0      .1       0   149.1    .045       0     164      .1       0
#XS Ineff= 2 , 0
                        190.3412         1873.28
Permanent Ineff=
       F       T
Bank Sta=149.1,164
XS Rating Curve= 0 ,0
Exp/Cntr(USF)=0,0
Exp/Cntr=0.3,0.1

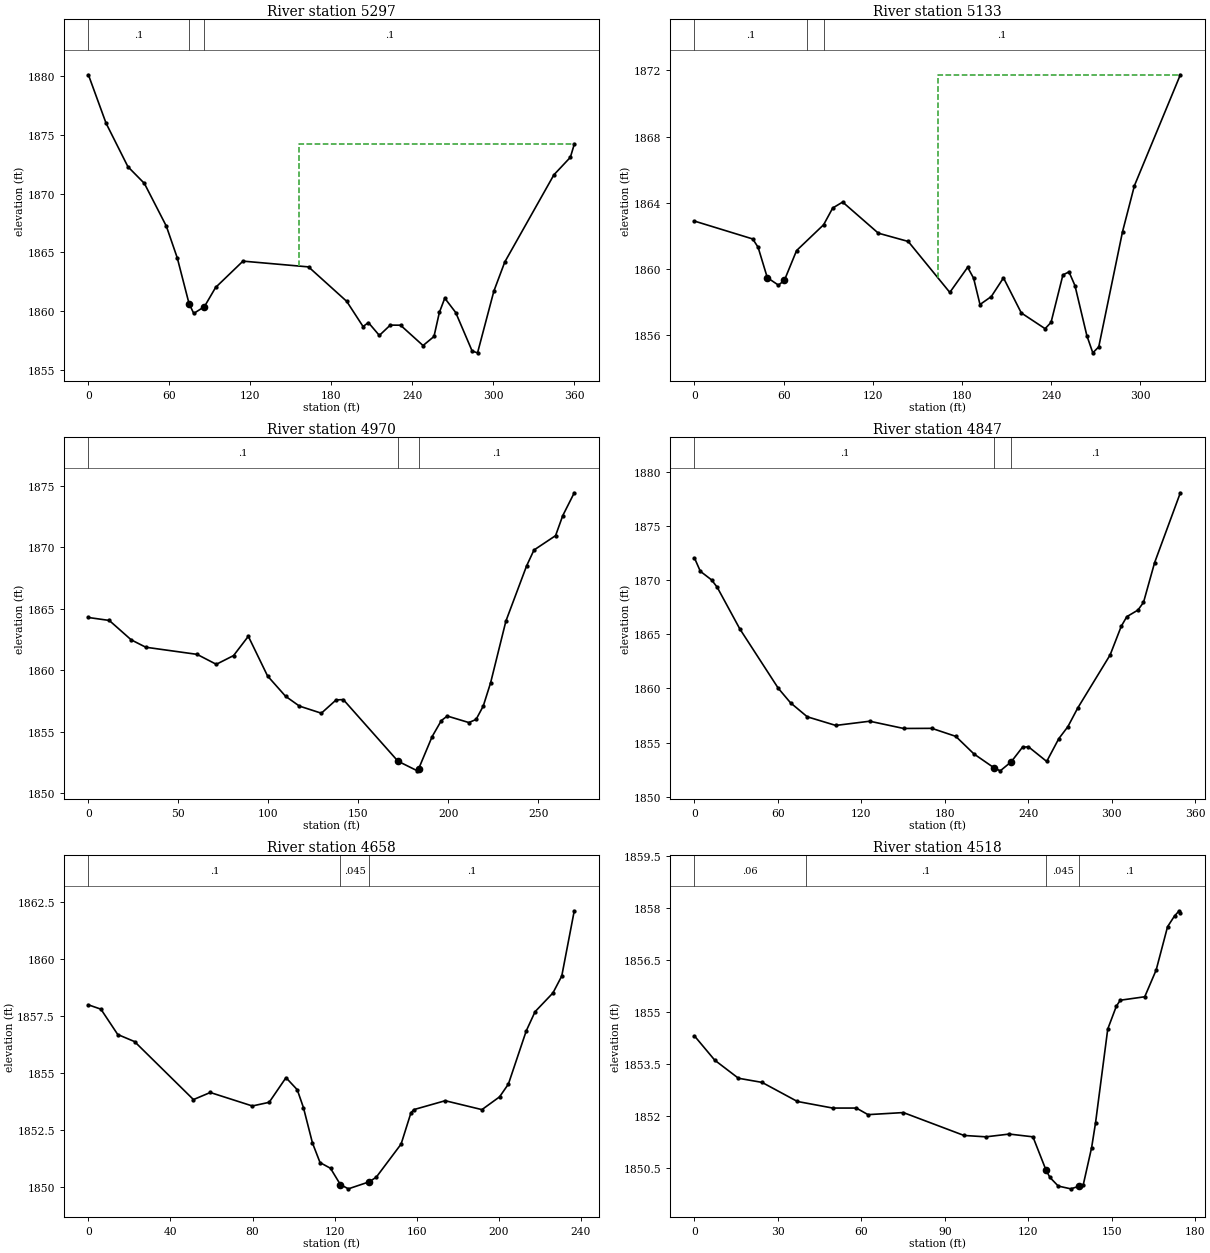
Type RM Length L Ch R = 1 ,5297    ,228.2,211.3,192.7
XS GIS Cut Line= 3
2193615.28148683675605.8598377542193731.94099185675626.275251132
2193971.09297714675590.791318356
#Sta/Elev= 30
       0 1880.11    13.1 1875.99    29.3 1872.29    41.5 1870.87    57.8 1867.23
    65.9 1864.53    74.61860.655    78.1 1859.81      861860.388    94.3 1862.02
   114.6 1864.26   163.2 1863.77   191.5 1860.84   203.6  1858.7   207.6 1859.03
   215.7 1857.94   223.8 1858.82   231.4 1858.81   248.1 1857.08   256.2 1857.85
   260.2  1859.9   264.2 1861.11   272.3 1859.89   284.5 1856.61   288.5 1856.46
   300.6 1861.71   308.7 1864.19   345.1  1871.6   357.3 1873.09   360.2  1874.2
#Mann= 3 ,-1,0
       0      .1       0    74.6    .045       0      86      .1       0
#XS Ineff= 2 , 0
                         156.267          1874.2
Permanent Ineff=
       F       T
Bank Sta=74.6,86
XS Rating Curve= 0 ,0
Exp/Cntr(USF)=0,0
Exp/Cntr=0.3,0.1

Type RM Length L Ch R = 1 ,5133    ,102.4,115.9,129.2
XS GIS Cut Line= 5
2193745.64317905675729.790973953 2193757.1587714675692.365298827
2193739.36194686675659.9122658512193730.98697061 675639.23654323
2193958.94290201675625.175931682
#Sta/Elev= 30
       0  1862.9    39.2 1861.82    42.8 1861.32      491859.483    56.5 1859.03
    60.51859.323    68.7 1861.12    86.9 1862.68      93 1863.69    99.7 1864.05
   123.7 1862.17   143.8 1861.67   171.8 1858.59   183.8 1860.11   187.8 1859.45
   192.1 1857.86   199.7 1858.34   207.9 1859.47   219.9 1857.35   235.9  1856.4
   239.9 1856.78   247.9 1859.65     252 1859.83     256    1859     264 1855.98
     268 1854.94     272  1855.3     288 1862.26     296 1865.04   326.9 1871.74
#Mann= 3 ,-1,0
       0      .1       0    75.4    .045       0    86.9      .1       0
#XS Ineff= 2 , 0
                        163.8677         1871.74
Permanent Ineff=
       F       T
Bank Sta=49,60.5
XS Rating Curve= 0 ,0
Exp/Cntr(USF)=0,0
Exp/Cntr=0.3,0.1

Type RM Length L Ch R = 1 ,4970    ,115.6,122.4,129.6
XS GIS Cut Line= 4
2193712.77685081 675748.558395242193850.18716528675723.359942156
2193912.39584633675708.3983606372193978.54178568675702.098747366
#Sta/Elev= 30
       0 1864.29    11.6 1864.05    23.8 1862.47    31.9 1861.87    60.4 1861.29
    71.1 1860.48    80.7 1861.19    88.9 1862.76    99.6 1859.53   109.6 1857.88
   117.3 1857.08   129.5  1856.5   137.7 1857.58   141.7 1857.61   172.11852.594
   182.9 1851.81   183.61851.982   191.1  1854.6   196.2  1855.9   199.5 1856.27
   211.5 1855.74   215.5 1855.99   219.5 1857.08   223.6 1858.98   232.1    1864
   243.6 1868.49   247.7 1869.78   259.7 1870.95   263.7 1872.58   270.1 1874.44
#Mann= 3 ,-1,0
       0      .1       0   172.1    .045       0   183.6      .1       0
Bank Sta=172.1,183.6
XS Rating Curve= 0 ,0
Exp/Cntr(USF)=0,0
Exp/Cntr=0.3,0.1

Type RM Length L Ch R = 1 ,4847    ,197.5,189.4,177.9
XS GIS Cut Line= 4
2193664.08632994 675779.365266032193835.83454543675809.626470645
 2193924.9494451675848.5129723182194002.72244845675846.892701415
#Sta/Elev= 30
       0 1872.07     4.2 1870.84    12.3 1870.04    16.3 1869.37    32.6 1865.51
    60.3 1860.01    69.1 1858.67    81.1 1857.38   101.6 1856.58     126 1856.97
   150.4  1856.3   170.7 1856.31   187.9 1855.57     201 1853.94   215.61852.644
   219.9 1852.38   227.81853.219   235.9 1854.57   240.2  1854.6   253.3 1853.25
     262 1855.36   268.5 1856.46   275.6 1858.19   298.9  1863.1   306.9 1865.75
   310.9 1866.64   318.9 1867.25   322.9 1867.96   330.9 1871.64   349.4  1878.1
#Mann= 3 ,-1,0
       0      .1       0   215.6    .045       0   227.8      .1       0
Bank Sta=215.6,227.8
XS Rating Curve= 0 ,0
Exp/Cntr(USF)=0,0
Exp/Cntr=0.3,0.1

Type RM Length L Ch R = 1 ,4658    ,129.8,140.3,149
XS GIS Cut Line= 4
2193750.24638028676023.9634118912193848.67783764676001.521039614
2193884.50688812675985.378280607 2193973.8826514675948.761778469
#Sta/Elev= 30
       0 1857.98     6.1 1857.79    14.3 1856.68    22.5 1856.37    51.2 1853.83
    59.4 1854.14    79.9 1853.55    88.1 1853.71    96.3 1854.79   101.8 1854.26
   104.8 1853.48   109.2 1851.93   112.9 1851.07     118 1850.82   122.81850.108
   126.7 1849.92   136.81850.225   140.3 1850.43   152.4 1851.88   157.2 1853.25
   158.6 1853.39   173.9 1853.78   191.8 1853.39   200.4 1853.95   204.7 1854.51
   213.4 1856.84   217.7 1857.68   226.4  1858.5   230.7 1859.24   236.8  1862.1
#Mann= 3 ,-1,0
       0      .1       0   122.8    .045       0   136.8      .1       0
Bank Sta=122.8,136.8
XS Rating Curve= 0 ,0
Exp/Cntr(USF)=0,0
Exp/Cntr=0.3,0.1

Type RM Length L Ch R = 1 ,4518    ,52.4,54.5,56
XS GIS Cut Line= 4
2193801.25712076676064.6659053182193912.32794108676103.395935582
2193950.22400098676121.9952287842193964.63845321676125.715087425
#Sta/Elev= 30
       0  1854.3     7.3  1853.6    15.8 1853.08    24.3 1852.96      37 1852.41
    49.7 1852.22    58.2 1852.22    62.4 1852.03    75.1 1852.09    96.9 1851.43
   104.8 1851.39   113.2 1851.47   121.7 1851.39   126.4 1850.43   127.8 1850.22
   130.8 1849.97   135.3 1849.89   138.41849.968   139.8 1850.01   142.8 1851.08
   144.2 1851.79   148.6  1854.5   151.7 1855.16   153.1 1855.33   161.9 1855.43
     166  1856.2   170.1 1857.45   172.6 1857.76   174.3 1857.91   174.7 1857.86
#Mann= 4 ,-1,0
       0     .06       0      40      .1       0   126.4    .045       0
   138.4      .1       0
Bank Sta=126.4,138.4
XS Rating Curve= 0 ,0
Exp/Cntr(USF)=0,0
Exp/Cntr=0.3,0.1

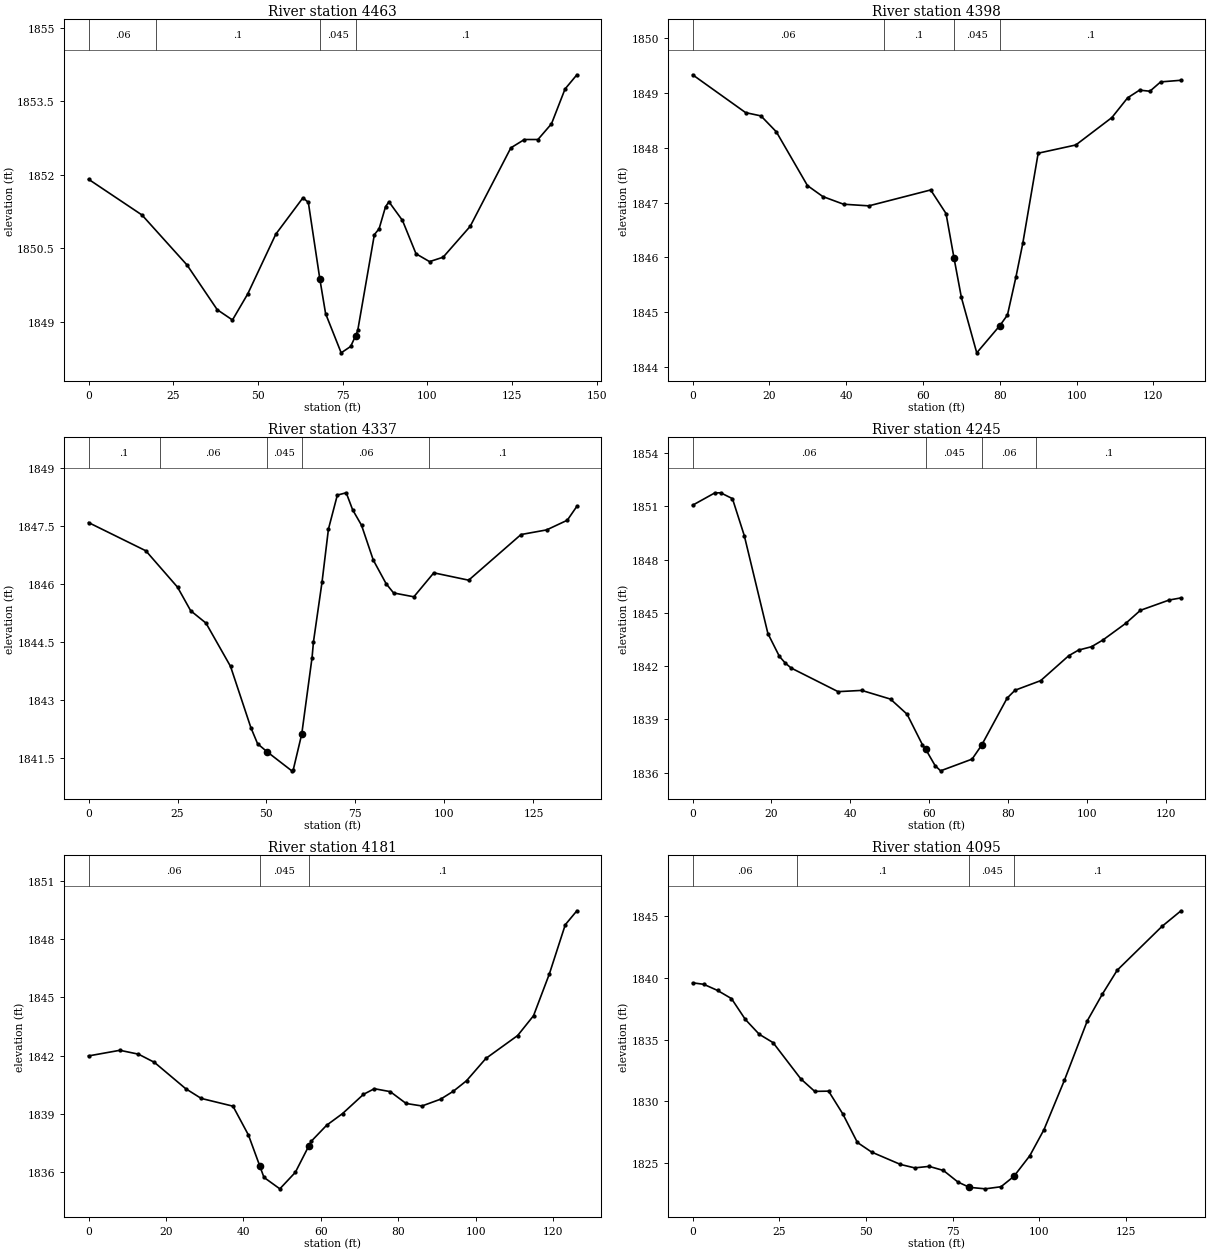
Type RM Length L Ch R = 1 ,4463    ,72.3,65.4,58
XS GIS Cut Line= 4
2193822.00496401676113.3273231512193879.43028177676141.458754119
2193897.33210147 676154.013277032193955.70429628676156.277676095
#Sta/Elev= 30
       0 1851.91    15.8 1851.18    29.1 1850.16      38 1849.25    42.5 1849.04
      47 1849.57    55.3 1850.79    63.3 1851.53    64.9 1851.44    68.31849.876
      70 1849.17    74.6 1848.37    77.4  1848.5    78.91848.723    79.5 1848.83
    84.4 1850.78    85.8  1850.9    87.7 1851.35    88.7 1851.45    92.7 1851.07
    96.7 1850.39   100.7 1850.23   104.7 1850.32   112.7 1850.95   124.7 1852.55
   128.7 1852.72   132.7 1852.72   136.7 1853.04   140.7 1853.75   144.2 1854.04
#Mann= 4 ,-1,0
       0     .06       0      20      .1       0    68.3    .045       0
    78.9      .1       0
Bank Sta=68.3,78.9
XS Rating Curve= 0 ,0
Exp/Cntr(USF)=0,0
Exp/Cntr=0.3,0.1

Type RM Length L Ch R = 1 ,4398    ,67.8,61.2,56.1
XS GIS Cut Line= 5
2193786.43183138676206.4628728092193806.06441865676208.271137426
2193847.39618132676204.654608193 2193879.6866209676202.846343576
2193903.96903147676179.597227073
#Sta/Elev= 25
       0 1849.33    13.8 1848.64    17.8 1848.58    21.8 1848.29    29.9 1847.31
    33.9 1847.11    39.3 1846.97    45.9 1846.94      62 1847.23      66  1846.8
    68.11845.981      70 1845.27      74 1844.26      801844.755      82 1844.95
    84.2 1845.64      86 1846.26      90  1847.9    99.8 1848.05   109.2 1848.55
   113.3 1848.91   116.4 1849.05   119.1 1849.03   121.9  1849.2   127.2 1849.23
#Mann= 4 ,-1,0
       0     .06       0   49.72      .1       0    68.1    .045       0
      80      .1       0
Bank Sta=68.1,80
XS Rating Curve= 0 ,0
Exp/Cntr(USF)=0,0
Exp/Cntr=0.3,0.1

Type RM Length L Ch R = 1 ,4337    ,87.3,91.2,93.8
XS GIS Cut Line= 4
2193825.00753474 676285.344509012193858.58959191676273.719950759
2193890.88003149676249.6958637072193940.94675918676214.122105056
#Sta/Elev= 30
       0 1847.59    16.1 1846.86      25 1845.92    28.7 1845.31      33 1844.99
    39.9 1843.87    45.6 1842.29    47.5 1841.87    50.11841.668    57.1 1841.17
    57.5 1841.19    59.9 1842.12    62.8  1844.1    63.2 1844.51    65.6 1846.05
    67.4 1847.42    69.9  1848.3    72.4 1848.36    74.2 1847.92    76.7 1847.52
      80 1846.62    83.6 1846.01    85.7 1845.77    91.4 1845.67      97 1846.29
   106.8  1846.1   121.5 1847.28   128.7  1847.4   134.5 1847.65   137.2 1848.01
#Mann= 5 ,-1,0
       0      .1       0      20     .06       0    50.1    .045       0
    59.9     .06       0   95.78      .1       0
Bank Sta=50.1,59.9
XS Rating Curve= 0 ,0
Exp/Cntr(USF)=0,0
Exp/Cntr=0.3,0.1

Type RM Length L Ch R = 1 ,4245    ,61.9,64.3,66.3
XS GIS Cut Line= 4
2193855.20977064676369.787399493 2193897.4026117676348.547465898
2193936.15113921676335.0572378042193966.00185669676315.539460987
#Sta/Elev= 30
       0 1851.06     5.6 1851.75     7.1 1851.76    10.1 1851.43    13.1 1849.35
    19.1 1843.83      22 1842.55    23.5 1842.17      25 1841.89    36.9 1840.56
    42.9 1840.63    50.2 1840.14    54.4 1839.29    58.3 1837.57    59.11837.324
    61.5  1836.4    62.9  1836.1    70.9 1836.76    73.31837.539    79.8  1840.2
    81.8 1840.64    88.3 1841.18    95.4 1842.58    97.9  1842.9   101.2 1843.09
   104.1 1843.47   109.9 1844.41   113.6 1845.14   120.9 1845.72   123.9 1845.84
#Mann= 4 ,-1,0
       0     .06       0    59.1    .045       0    73.3     .06       0
   87.24      .1       0
Bank Sta=59.1,73.3
XS Rating Curve= 0 ,0
Exp/Cntr(USF)=0,0
Exp/Cntr=0.3,0.1

Type RM Length L Ch R = 1 ,4181    ,86.6,86.3,83.8
XS GIS Cut Line= 4
2193887.39163591676409.7153034042193924.59872679676403.691298213
2193952.23828001676399.7934125022194011.06091893676385.619282642
#Sta/Elev= 30
       0 1841.98     8.1 1842.27    12.9 1842.07      17 1841.65    25.1 1840.29
    29.1 1839.79    37.3 1839.39    41.3  1837.9    44.21836.319    45.3 1835.72
    49.4 1835.13    53.4 1835.98    56.9 1837.35    57.5 1837.58    61.5 1838.41
    65.6 1839.01      71    1840    73.8 1840.29    77.9 1840.14      82 1839.53
    86.1  1839.4    90.9 1839.75    94.2 1840.16    97.6  1840.7   102.6 1841.85
   110.8 1843.03   114.9 1844.05     119 1846.21   123.1 1848.74   126.1 1849.46
#Mann= 3 ,-1,0
       0     .06       0    44.2    .045       0    56.9      .1       0
Bank Sta=44.2,56.9
XS Rating Curve= 0 ,0
Exp/Cntr(USF)=0,0
Exp/Cntr=0.3,0.1

Type RM Length L Ch R = 1 ,4095    ,102.1,102,100.4
XS GIS Cut Line= 4
2193908.97174862676470.731388917 2193949.4424329676472.166519565
2194016.89357337676454.083873397 2194045.3091602 676443.17688047
#Sta/Elev= 30
       0  1839.6     3.2 1839.48     7.2 1838.98    11.2 1838.32    15.2 1836.63
    19.2 1835.43    23.2 1834.75    31.2 1831.81    35.2  1830.8    39.2 1830.82
    43.3 1828.97    47.5 1826.66    51.6 1825.88    59.9 1824.88      64  1824.6
    68.2 1824.72    72.3 1824.39    76.5 1823.45    79.81823.021    84.4  1822.9
    88.9 1823.07    92.61823.905    97.2 1825.58   101.3  1827.7   107.2 1831.71
   113.8 1836.53   118.1 1838.67   122.4 1840.62   135.3 1844.17   140.8 1845.44
#Mann= 4 ,-1,0
       0     .06       0      30      .1       0    79.8    .045       0
    92.6      .1       0
Bank Sta=79.8,92.6
XS Rating Curve= 0 ,0
Exp/Cntr(USF)=0,0
Exp/Cntr=0.3,0.1

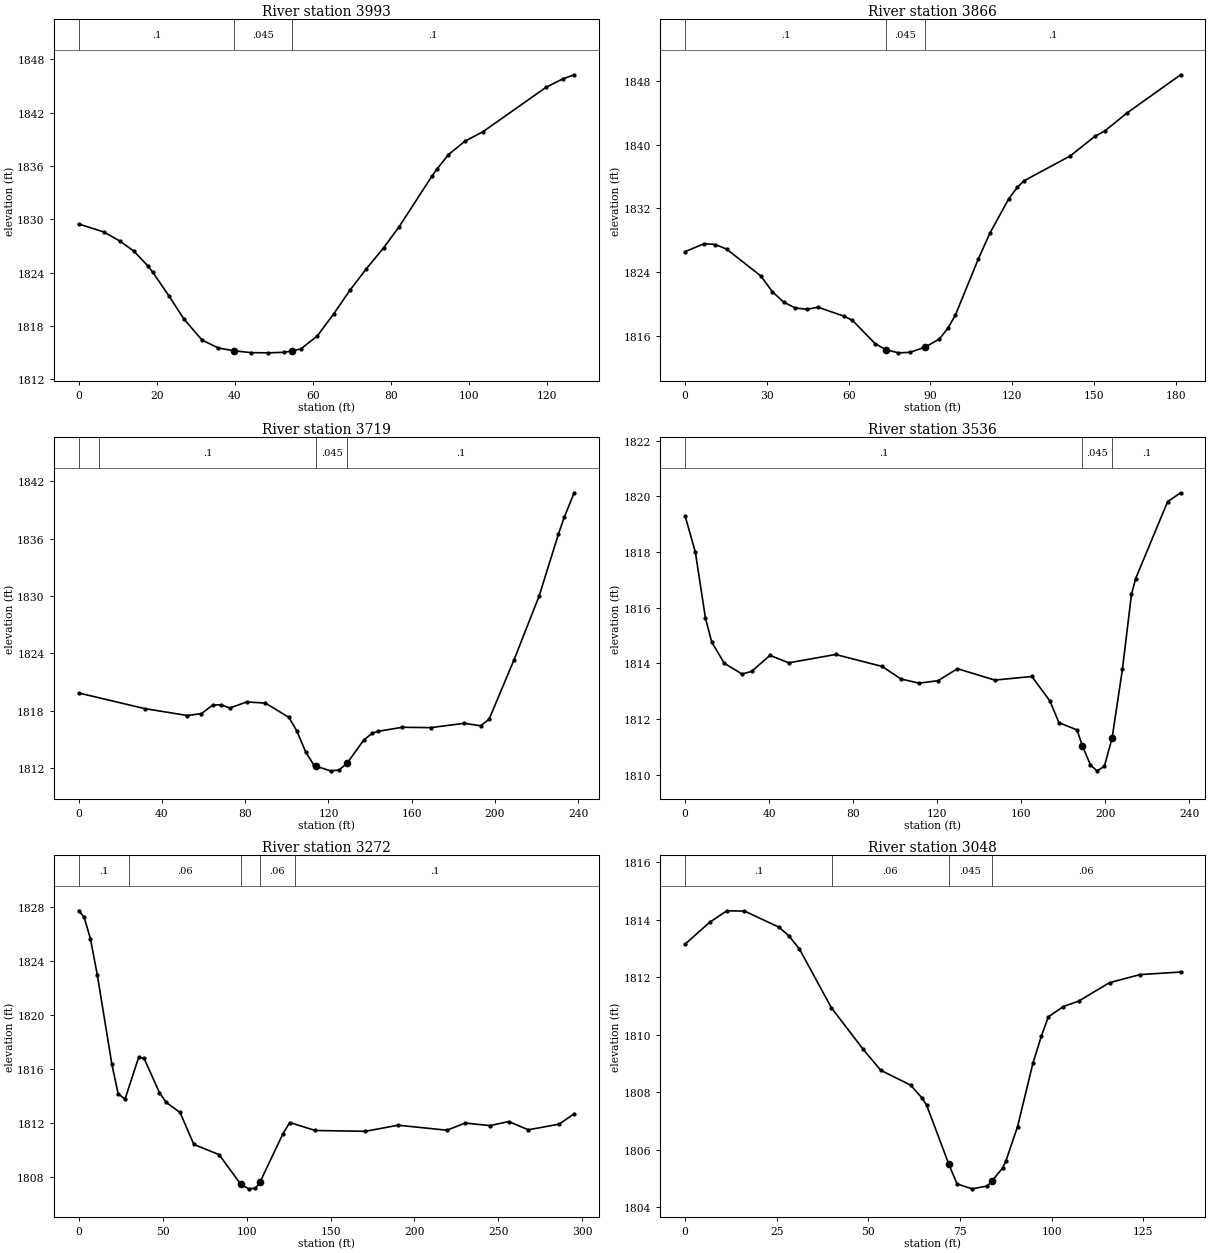
Type RM Length L Ch R = 1 ,3993    ,126.1,126.3,126.2
XS GIS Cut Line= 3
2193962.12472899676569.5567742782194032.99537829676546.370697656
2194082.86731668676530.621664479
#Sta/Elev= 30
       0 1829.47     6.4 1828.58    10.6 1827.54    14.1 1826.43    17.8 1824.72
      19 1824.03    23.2 1821.33    26.9 1818.81    31.6 1816.41    35.8 1815.51
    39.81815.204    44.2 1814.99    48.5 1814.97    52.7 1815.03    54.71815.198
    56.9 1815.41    61.1 1816.86    65.3 1819.34    69.5 1822.03    73.7 1824.44
    78.1 1826.78    82.1 1829.18    90.5 1834.87    91.8 1835.67    94.7 1837.27
    98.9 1838.78   103.6 1839.87   119.8 1844.88     124  1845.8   126.9 1846.26
#Mann= 3 ,-1,0
       0      .1       0    39.8    .045       0    54.7      .1       0
Bank Sta=39.8,54.7
XS Rating Curve= 0 ,0
Exp/Cntr(USF)=0,0
Exp/Cntr=0.3,0.1

Type RM Length L Ch R = 1 ,3866    ,144,147.5,150.9
XS GIS Cut Line= 4
2193965.33839964676698.7123019152193983.70146987676694.391579507
2194082.53799495676662.5262517472194138.70738626676644.163181513
#Sta/Elev= 30
       0 1826.55       7 1827.56    11.1 1827.45    15.2 1826.88    27.8 1823.49
      32 1821.52    36.2 1820.19    40.4 1819.47    44.6  1819.3    48.8 1819.56
    58.3 1818.43    61.4 1817.91    69.8 1814.95    73.61814.232    78.2 1813.82
    82.4 1813.88      88 1814.53    93.3 1815.57    96.5 1816.96    99.2  1818.6
   107.6 1825.65   111.8 1828.86   118.7 1833.18   121.9 1834.66   124.4 1835.48
   141.3  1838.6   150.4 1841.08   153.9 1841.72   162.3 1844.05   181.8 1848.81
#Mann= 3 ,-1,0
       0      .1       0    73.6    .045       0      88      .1       0
Bank Sta=73.6,88
XS Rating Curve= 0 ,0
Exp/Cntr(USF)=0,0
Exp/Cntr=0.3,0.1

Type RM Length L Ch R = 1 ,3719    ,178,183.3,187.7
XS GIS Cut Line= 4
2193924.98729095676803.0332830732194017.88282272676821.396353307
2194077.29275583676819.7760824042194161.00675249676813.835089093
#Sta/Elev= 30
       0 1819.86    31.8 1818.22    52.2  1817.5      59  1817.7    64.4  1818.6
    68.5 1818.62    72.6 1818.28    80.7 1818.92    89.7  1818.8     101  1817.3
   104.9 1815.84     109 1813.71     113 1812.31   114.21812.178     121 1811.71
     125 1811.79   128.91812.492     137 1814.95     141 1815.64   143.9 1815.85
   155.5 1816.27     169 1816.23   185.1 1816.68   193.1 1816.43   197.1  1817.1
   209.1 1823.32   221.2 1830.02   230.4 1836.46   233.2 1838.23     238 1840.81
#Mann= 4 ,-1,0
       0     .06       0      10      .1       0   114.2    .045       0
   128.9      .1       0
Bank Sta=114.2,128.9
XS Rating Curve= 0 ,0
Exp/Cntr(USF)=0,0
Exp/Cntr=0.3,0.1

Type RM Length L Ch R = 1 ,3536    ,260.9,263.2,262.2
XS GIS Cut Line= 3
2193959.54527465676836.8002971862194034.76291959 676991.60821863
 2194093.8903023677015.144361262
#Sta/Elev= 30
       0  1819.3     4.9 1817.99     9.7 1815.62    12.7 1814.76    18.7    1814
    27.1 1813.62    31.6 1813.71    40.4 1814.29    49.3 1814.02    71.6 1814.32
    93.8 1813.89   102.7 1813.44   111.3 1813.29   120.4 1813.38   129.6 1813.81
   147.4  1813.4     165 1813.53   173.6 1812.65   177.9 1811.87   186.5 1811.61
   189.11811.025   192.9 1810.35     196 1810.14   199.5  1810.3   203.21811.324
   208.1 1813.79   212.4 1816.48   214.4 1817.05   229.6 1819.81   235.8 1820.13
#Mann= 3 ,-1,0
       0      .1       0   189.1    .045       0   203.2      .1       0
Bank Sta=189.1,203.2
XS Rating Curve= 0 ,0
Exp/Cntr(USF)=0,0
Exp/Cntr=0.3,0.1

Type RM Length L Ch R = 1 ,3272    ,227.8,224,218.2
XS GIS Cut Line= 4
2193809.34350308676940.1760905982193863.03694126 676952.92041596
2193935.04538841676967.3414521012194035.16231799677100.288330163
#Sta/Elev= 30
       0  1827.7     3.2 1827.25       7 1825.65    11.1 1822.97    19.8 1816.36
    23.5  1814.2    27.6 1813.78    35.8 1816.89      39 1816.79    48.1 1814.27
    52.2 1813.54    60.4  1812.8    68.6 1810.44    83.6 1809.69    96.41807.524
   101.2 1807.16   105.3  1807.2     1081807.654   121.6 1811.21   125.7 1812.06
   140.9 1811.47   170.7 1811.41   190.3 1811.86   219.3 1811.49   230.2 1812.02
     245 1811.83   256.1 1812.13   267.8 1811.52   286.2 1811.94   295.1 1812.71
#Mann= 5 ,-1,0
       0      .1       0      30     .06       0    96.4    .045       0
     108     .06       0  128.62      .1       0
Bank Sta=96.4,108
XS Rating Curve= 0 ,0
Exp/Cntr(USF)=0,0
Exp/Cntr=0.3,0.1

Type RM Length L Ch R = 1 ,3048    ,157.1,143.8,131.9
XS GIS Cut Line= 4
2193902.47959824677178.4576114772193944.41162822 677152.12774785
2193994.83896192677138.1085305992194026.86769746677128.707340532
#Sta/Elev= 29
       0 1813.15     6.7 1813.91    11.4 1814.31    16.2  1814.3    25.6 1813.74
    28.3 1813.44    31.2 1812.98    39.9 1810.94    48.6 1809.49    53.4 1808.76
    61.5 1808.25    64.7 1807.79    65.9 1807.55    71.91805.513    74.2 1804.81
    78.3 1804.64    82.5 1804.74    83.71804.909    86.6 1805.36    87.5  1805.6
    90.7  1806.8    94.9 1809.01    97.2 1809.95    99.1 1810.62   103.2 1810.98
   107.4 1811.17   115.8 1811.81   124.1 1812.09   135.2 1812.18
#Mann= 4 ,-1,0
       0      .1       0      40     .06       0    71.9    .045       0
    83.7     .06       0
Bank Sta=71.9,83.7
XS Rating Curve= 0 ,0
Exp/Cntr(USF)=0,0
Exp/Cntr=0.3,0.1