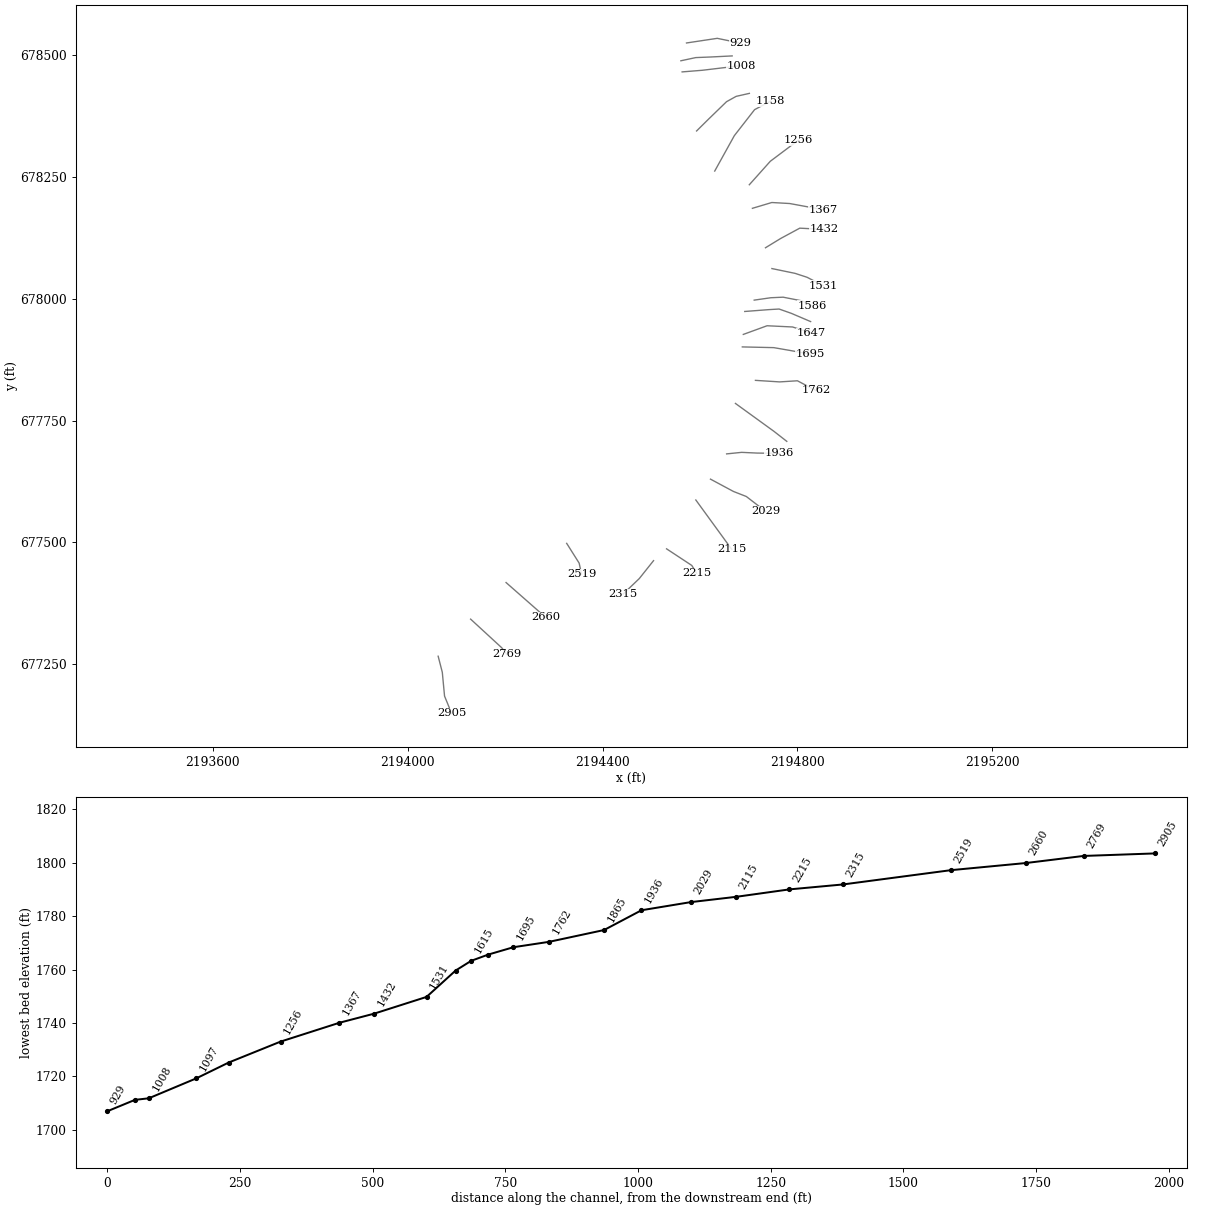
HEC-RAS study INDIANCPRN.prj: INDIANCPRN

--- INDIANCPRN.g01 (geometry) --- (continued)

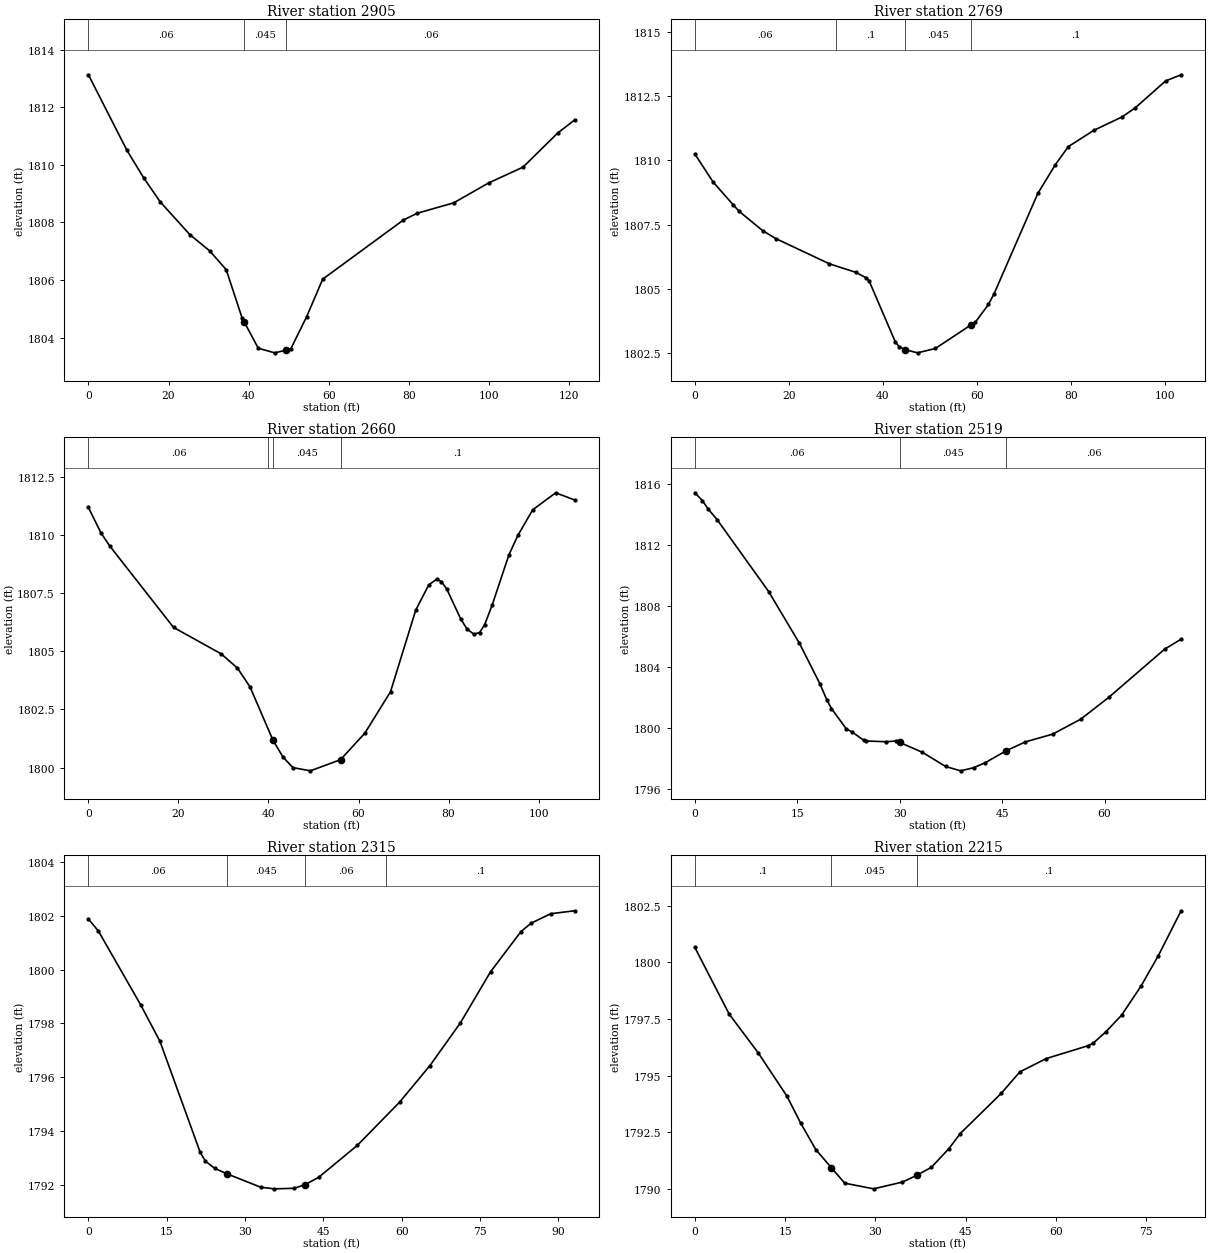
Type RM Length L Ch R = 1 ,2905    ,126.4,135.2,141.7
XS GIS Cut Line= 4
 2194062.6654347677266.5091106972194071.16991262677233.554258774
2194075.77650482677184.6535107592194090.30498793 677149.21818611
#Sta/Elev= 22
       0 1813.13     9.6 1810.51    13.8 1809.55    17.9 1808.72    25.3 1807.58
    30.3 1807.01    34.4 1806.36    38.4 1804.67    38.91804.545    42.4 1803.63
    46.5 1803.47    49.41803.564    50.5  1803.6    54.5 1804.73    58.5 1806.03
    78.6 1808.08    82.1 1808.32    91.2 1808.68    99.9 1809.37   108.5 1809.92
   117.2 1811.11   121.4 1811.56
#Mann= 3 ,-1,0
       0     .06       0    38.9    .045       0    49.4     .06       0
Bank Sta=38.9,49.4
XS Rating Curve= 0 ,0
Exp/Cntr(USF)=0,0
Exp/Cntr=0.3,0.1

Type RM Length L Ch R = 1 ,2769    ,108.6,109.1,108.7
XS GIS Cut Line= 3
2194129.27799046677342.6348386232194193.06157483677283.953941005
2194203.26694833677270.559388288
#Sta/Elev= 27
       0 1810.24     3.9 1809.15     8.1 1808.28     9.4 1808.02    14.4 1807.27
    17.2 1806.96    28.6 1805.98    34.2 1805.65    36.5 1805.43    37.1 1805.31
    42.7 1802.93    43.5 1802.76    44.71802.646    47.4 1802.52    51.2 1802.69
    58.71803.596    59.7 1803.71    62.5  1804.4    63.7 1804.82      73 1808.71
    76.7 1809.82    79.5 1810.53    84.9 1811.16    90.9 1811.68    93.7 1812.03
   100.2 1813.08   103.5 1813.32
#Mann= 4 ,-1,0
       0     .06       0      30      .1       0    44.7    .045       0
    58.7      .1       0
Bank Sta=44.7,58.7
XS Rating Curve= 0 ,0
Exp/Cntr(USF)=0,0
Exp/Cntr=0.3,0.1

Type RM Length L Ch R = 1 ,2660    ,143.8,140.7,135.3
XS GIS Cut Line= 2
2194202.03419762677417.6875853512194283.14171848677346.423210224
#Sta/Elev= 30
       0 1811.19     2.8 1810.09     4.7 1809.54    18.9 1806.03    29.5 1804.89
    33.1 1804.28    35.9 1803.47      411801.172    43.2 1800.46    45.4    1800
    49.3 1799.86      56 1800.34    61.4 1801.48    67.1 1803.26    72.7 1806.77
    75.6 1807.86    77.4 1808.11    78.4    1808    79.6 1807.68    82.7 1806.39
    84.1 1805.96    85.6 1805.74    86.9 1805.81      88 1806.14    89.7    1807
    93.4 1809.15    95.4 1809.99    98.7 1811.09   103.8 1811.82     108 1811.51
#Mann= 4 ,-1,0
       0     .06       0      40      .1       0      41    .045       0
      56      .1       0
Bank Sta=41,56
XS Rating Curve= 0 ,0
Exp/Cntr(USF)=0,0
Exp/Cntr=0.3,0.1

Type RM Length L Ch R = 1 ,2519    ,215.6,203.9,188.3
XS GIS Cut Line= 3
2194326.43857843 677498.097386132194352.01260658 677457.54059401
 2194356.9207534677434.808124541
#Sta/Elev= 28
       0 1815.45     1.1 1814.94     1.9 1814.41     3.3 1813.66    10.8 1808.97
    15.3 1805.58    18.3 1802.92    19.3 1801.88      20 1801.29    22.2 1799.94
      23 1799.76    24.7 1799.21    25.1 1799.16      28 1799.11    29.5 1799.16
      301799.064    33.3 1798.42    36.7 1797.49    38.9  1797.2    40.8  1797.4
    42.5 1797.73    45.61798.522    48.4  1799.1    52.4 1799.61    56.5 1800.59
    60.6 1802.02    68.8 1805.19    71.2 1805.84
#Mann= 3 ,-1,0
       0     .06       0      30    .045       0    45.6     .06       0
Bank Sta=30,45.6
XS Rating Curve= 0 ,0
Exp/Cntr(USF)=0,0
Exp/Cntr=0.3,0.1

Type RM Length L Ch R = 1 ,2315    ,78.5,100.6,119.3
XS GIS Cut Line= 3
2194504.69158155677462.6711435552194475.39769476677425.844543016
2194442.12820904677394.039751641
#Sta/Elev= 22
       0 1801.88     1.9 1801.44      10 1798.69    13.7 1797.33    21.4  1793.2
    22.4 1792.87    24.2  1792.6    26.61792.393      33  1791.9    35.6 1791.84
    39.4 1791.86    41.51791.997    44.1 1792.27    51.5 1793.46    59.6 1795.07
    65.4 1796.43    71.2 1798.01      77 1799.92    82.8 1801.41    84.7 1801.72
    88.5 1802.08    93.1 1802.19
#Mann= 4 ,-1,0
       0     .06       0    26.6    .045       0    41.5     .06       0
   57.06      .1       0
Bank Sta=26.6,41.5
XS Rating Curve= 0 ,0
Exp/Cntr(USF)=0,0
Exp/Cntr=0.3,0.1

Type RM Length L Ch R = 1 ,2215    ,104.1,100.2,95.5
XS GIS Cut Line= 3
2194531.37812617 677486.873642862194583.16553318677452.788113156
2194592.95806105677436.781096445
#Sta/Elev= 24
       0 1800.65     5.7 1797.71    10.5 1796.01    15.3 1794.09    17.6 1792.89
    20.1 1791.73    22.71790.928    24.9 1790.25    29.7    1790    34.5  1790.3
    36.91790.599    39.3 1790.95    42.2 1791.77    44.1 1792.44    50.9 1794.21
      54 1795.16    58.4 1795.75    65.4 1796.32    66.2 1796.43    68.3 1796.93
    70.9 1797.66    74.1 1798.93      77 1800.28    80.8 1802.27
#Mann= 3 ,-1,0
       0      .1       0    22.7    .045       0    36.9      .1       0
Bank Sta=22.7,36.9
XS Rating Curve= 0 ,0
Exp/Cntr(USF)=0,0
Exp/Cntr=0.3,0.1

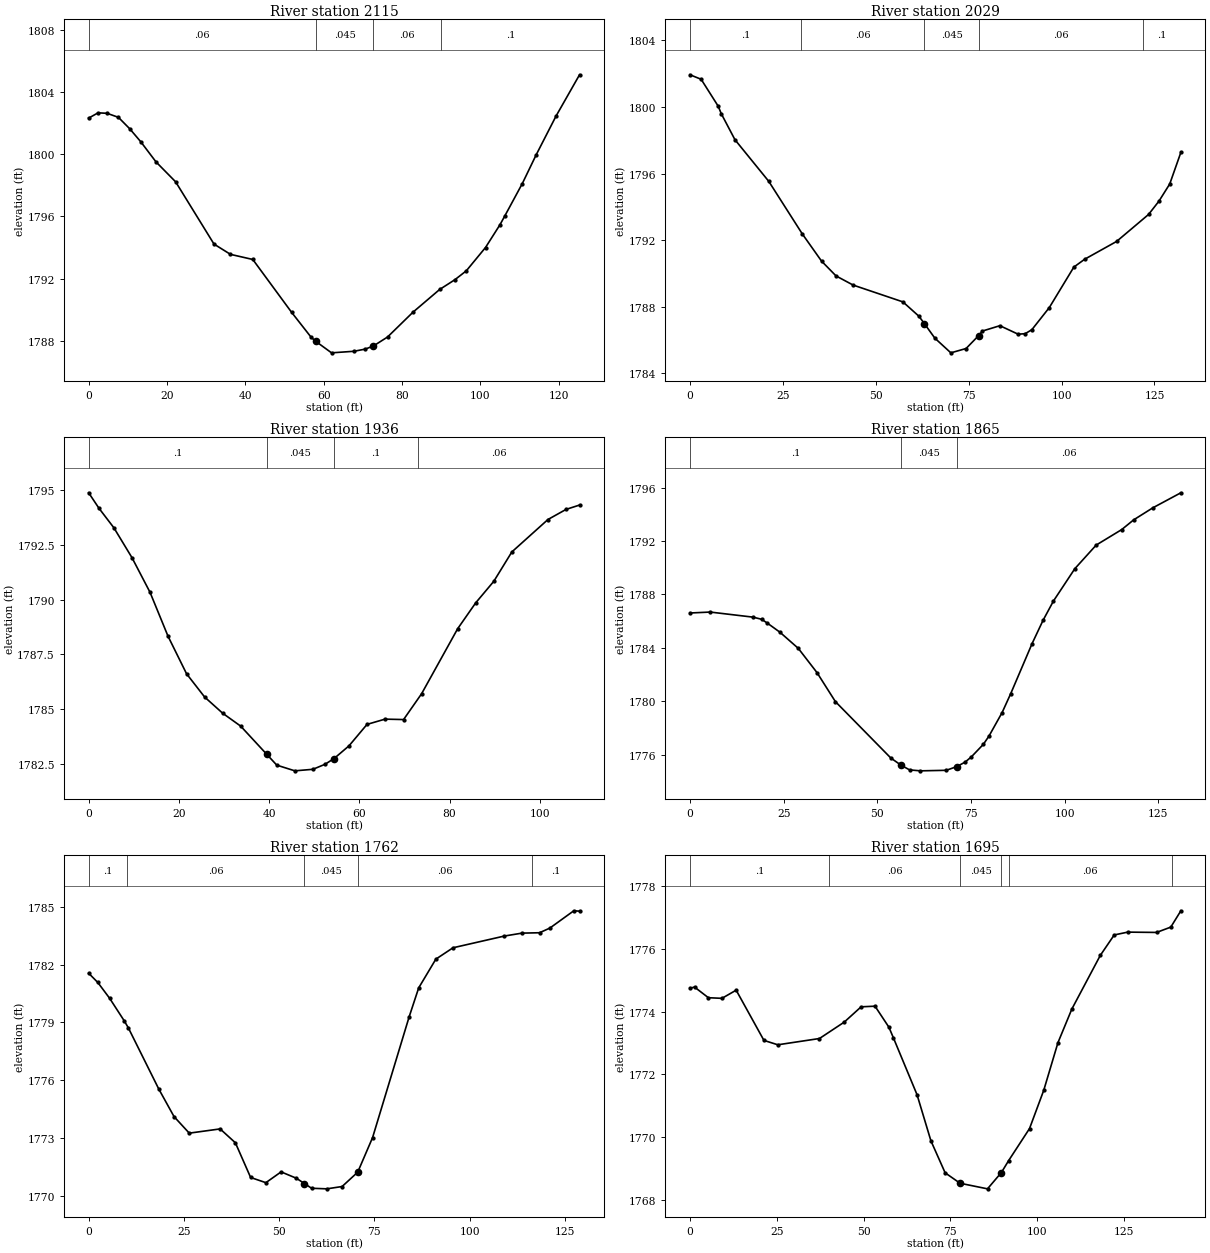
Type RM Length L Ch R = 1 ,2115    ,78.3,85.5,92.1
XS GIS Cut Line= 2
2194591.45671897677587.0941865472194665.16219424677485.749158052
#Sta/Elev= 30
       0 1802.33     2.4 1802.67     4.7 1802.64     7.6 1802.38    10.5 1801.64
    13.3 1800.81    17.2 1799.51    22.2 1798.23      32 1794.22    36.2 1793.56
    41.9 1793.23    51.8 1789.83    56.8 1788.22      581787.955      62 1787.22
    67.7 1787.32    70.6 1787.46    72.71787.663    76.3 1788.24    82.8 1789.84
    89.6  1791.3    93.5 1791.93    96.4  1792.5   101.3    1794     105 1795.47
   106.2 1796.02   110.7 1798.12   114.2 1799.95   119.3 1802.46   125.3 1805.12
#Mann= 4 ,-1,0
       0     .06       0      58    .045       0    72.7     .06       0
      90      .1       0
Bank Sta=58,72.7
XS Rating Curve= 0 ,0
Exp/Cntr(USF)=0,0
Exp/Cntr=0.3,0.1

Type RM Length L Ch R = 1 ,2029    ,88.4,93.1,96.7
XS GIS Cut Line= 4
 2194621.5205536677629.8991193992194668.59283887 677604.64081999
2194694.99924279677594.3078793222194734.89587482677563.596083449
#Sta/Elev= 30
       0 1801.94       3 1801.67     7.6 1800.05     8.4 1799.61    12.1 1798.04
    21.2 1795.54    30.2 1792.39    35.4 1790.75    39.3 1789.86    43.9 1789.31
    57.3  1788.3    61.6 1787.44    63.11786.988    65.9 1786.12    70.2 1785.24
    74.3  1785.5    77.71786.281    78.7 1786.55    83.4 1786.87    88.3 1786.36
    90.2 1786.39      92 1786.63    96.7 1787.96   103.3 1790.39   106.2 1790.86
   114.8 1791.93   123.4 1793.55   126.2 1794.35   129.1 1795.38   132.1 1797.28
#Mann= 5 ,-1,0
       0      .1       0      30     .06       0    63.1    .045       0
    77.7     .06       0  121.78      .1       0
Bank Sta=63.1,77.7
XS Rating Curve= 0 ,0
Exp/Cntr(USF)=0,0
Exp/Cntr=0.3,0.1

Type RM Length L Ch R = 1 ,1936    ,77.6,70.6,63.2
XS GIS Cut Line= 4
2194654.61873345677681.7178243082194685.37731458677684.856455036
2194717.39134801677683.3917606962194763.21535663 677682.76403455
#Sta/Elev= 28
       0 1794.88     2.3 1794.17     5.6 1793.28     9.6 1791.92    13.6 1790.34
    17.6 1788.33    21.7 1786.62    25.7 1785.56    29.7 1784.82    33.7 1784.23
    39.51782.939    41.7 1782.45    45.7 1782.19    49.7 1782.26    52.4 1782.49
    54.41782.752    57.7 1783.33    61.7 1784.31    65.7 1784.55    69.8 1784.53
    73.8 1785.71    81.8 1788.68    85.8 1789.86    89.8 1790.84    93.8 1792.18
   101.8 1793.66   105.8 1794.12   108.8 1794.32
#Mann= 4 ,-1,0
       0      .1       0    39.5    .045       0    54.4      .1       0
   72.97     .06       0
Bank Sta=39.5,54.4
XS Rating Curve= 0 ,0
Exp/Cntr(USF)=0,0
Exp/Cntr=0.3,0.1

Type RM Length L Ch R = 1 ,1865    ,95.2,103.7,111.7
XS GIS Cut Line= 3
2194672.73572944677785.2467247732194751.95494123677727.841498843
2194778.07431903677707.462643638
#Sta/Elev= 30
       0 1786.61     5.4 1786.68    16.8  1786.3    19.1 1786.14    20.6 1785.86
      24 1785.17    28.9 1783.96    33.9 1782.14    38.8 1779.97    53.6 1775.74
    56.31775.208    58.6 1774.85    61.5 1774.78    68.4 1774.82    71.2  1775.1
    73.4 1775.43    75.1 1775.83    78.3 1776.77    79.8 1777.39    83.3 1779.15
    85.6 1780.57    91.3 1784.32    94.2 1786.05      97 1787.51   102.7 1789.93
   108.4  1791.7   115.2 1792.86   118.4 1793.59   123.5 1794.49     131 1795.62
#Mann= 3 ,-1,0
       0      .1       0    56.3    .045       0    71.2     .06       0
Bank Sta=56.3,71.2
XS Rating Curve= 0 ,0
Exp/Cntr(USF)=0,0
Exp/Cntr=0.3,0.1

Type RM Length L Ch R = 1 ,1762    ,69.6,67,64
XS GIS Cut Line= 4
2194713.78046598677832.6060361662194763.43598641 677829.44874874
2194799.88830488677831.7449577772194837.48872786677811.940154831
#Sta/Elev= 30
       0 1781.55     2.4 1781.07     5.5 1780.25     9.3 1779.09    10.4 1778.72
    18.4 1775.54    22.4 1774.11    26.4 1773.25    34.5 1773.47    38.5 1772.75
    42.5 1770.95    46.5 1770.68    50.5 1771.24    54.5 1770.91    56.61770.637
    58.5 1770.39    62.5 1770.36    66.5 1770.48    70.61771.226    74.5 1773.02
    84.1 1779.29    86.6 1780.79    91.1 1782.28    95.6 1782.87   109.1 1783.48
   113.7 1783.63   118.3 1783.65     121 1783.89   127.3 1784.79   128.8 1784.77
#Mann= 5 ,-1,0
       0      .1       0      10     .06       0    56.6    .045       0
    70.6     .06       0  116.28      .1       0
Bank Sta=56.6,70.6
XS Rating Curve= 0 ,0
Exp/Cntr(USF)=0,0
Exp/Cntr=0.3,0.1

Type RM Length L Ch R = 1 ,1695    ,45.9,47.4,48.7
XS GIS Cut Line= 4
2194686.84560285677901.238233249 2194751.2921538 677899.77353891
2194785.18936566677893.9147615512194827.03777536677886.172805756
#Sta/Elev= 30
       0 1774.74     1.3 1774.78     5.3 1774.44     9.2 1774.42    13.3 1774.68
    21.3 1773.08    25.3 1772.94    37.3 1773.14    44.4 1773.66    49.3 1774.15
    53.3 1774.17    57.3  1773.5    58.6 1773.16    65.4 1771.35    69.4 1769.88
    73.5 1768.86    77.81768.528    85.7 1768.35    89.7 1768.87    91.81769.252
    97.8 1770.27   101.9 1771.49     106 1773.01     110 1774.08   118.2 1775.79
   122.2 1776.44   126.1 1776.53   134.4 1776.52   138.5 1776.69   141.4 1777.21
#Mann= 6 ,-1,0
       0      .1       0      40     .06       0    77.8    .045       0
    89.7     .06       0    91.8     .06       0  138.86      .1       0
Bank Sta=77.8,89.7
XS Rating Curve= 0 ,0
Exp/Cntr(USF)=0,0
Exp/Cntr=0.3,0.1

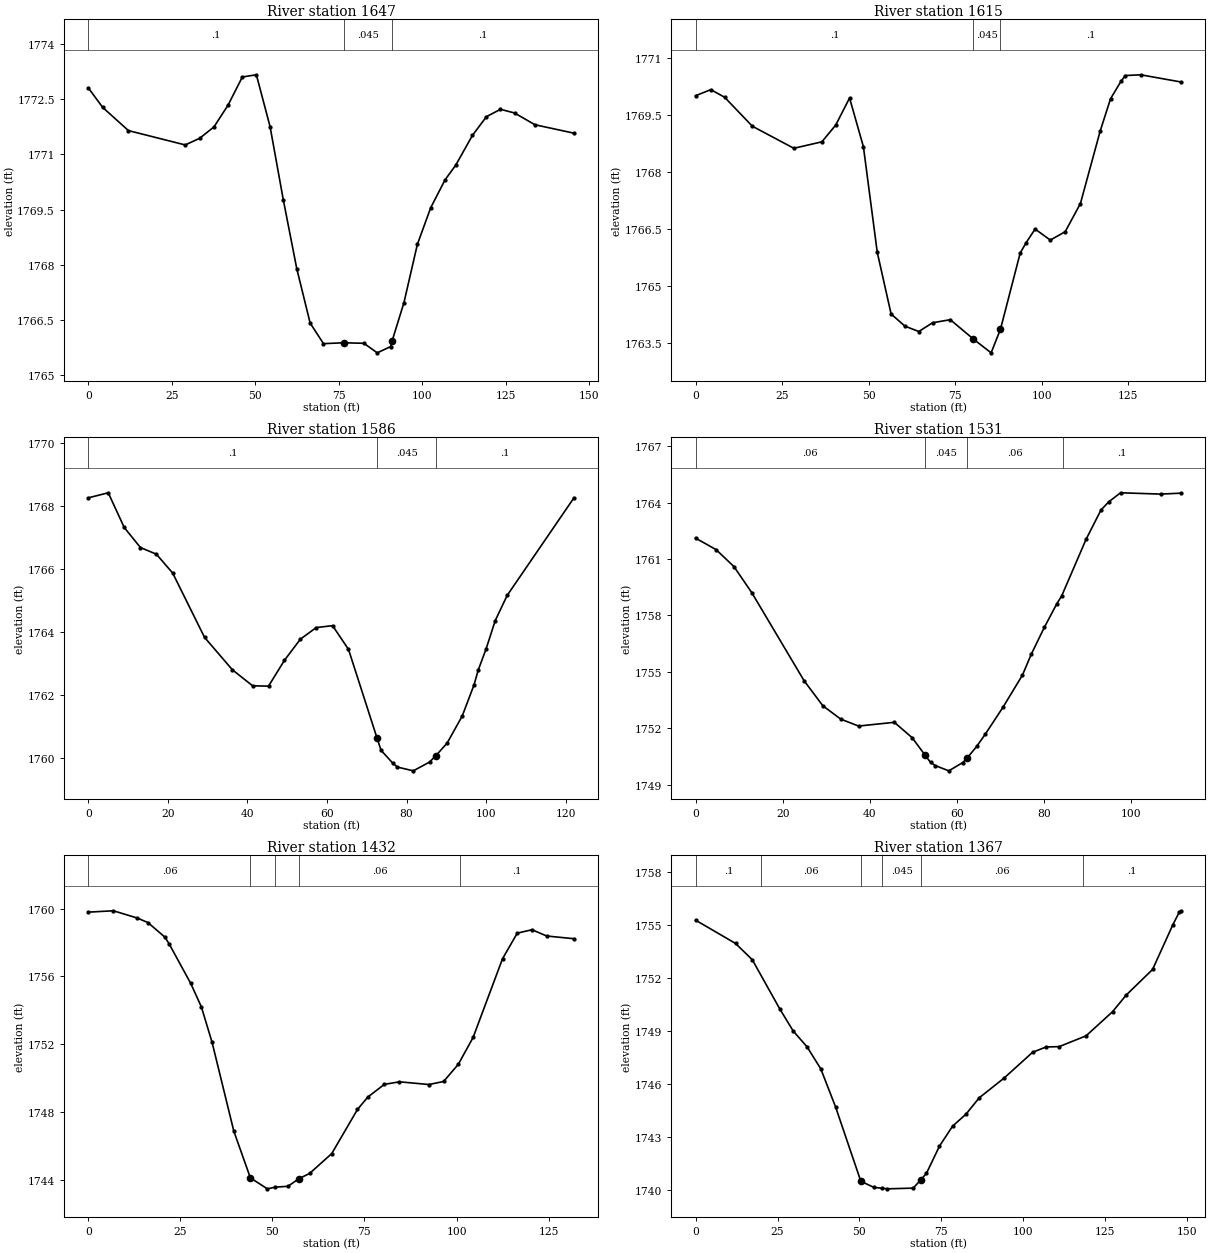
Type RM Length L Ch R = 1 ,1647    ,35.5,32.3,30
XS GIS Cut Line= 4
2194688.89726563 677926.886441712194737.65066293677944.672015834
2194789.96117506677942.1611112512194829.08943813 677929.60658834
#Sta/Elev= 30
       0 1772.81     4.3 1772.28      12 1771.65      29 1771.26    33.3 1771.44
    37.6 1771.75    41.8 1772.34    46.1 1773.11    50.3 1773.17    54.4 1771.76
    58.4 1769.75    62.4 1767.89    66.4 1766.41    70.4 1765.85    76.41765.874
    82.5 1765.86    86.5  1765.6    90.5 1765.77    90.91765.909    94.5 1766.97
    98.5 1768.55   102.5 1769.55   106.8 1770.31     110 1770.71     115 1771.52
   119.2 1772.03   123.4 1772.23   127.6 1772.13   133.7 1771.81   145.4 1771.58
#Mann= 3 ,-1,0
       0      .1       0    76.4    .045       0    90.9      .1       0
Bank Sta=76.4,90.9
XS Rating Curve= 0 ,0
Exp/Cntr(USF)=0,0
Exp/Cntr=0.3,0.1

Type RM Length L Ch R = 1 ,1615    ,27.6,29.4,32.5
XS GIS Cut Line= 5
2194691.82665431677973.9659026262194740.78929366677977.732259499
2194762.34122466 677978.987711792194787.24102843677970.199545753
2194826.99701765677953.250939823
#Sta/Elev= 30
       0    1770     4.4 1770.16     8.4 1769.96    16.4  1769.2    28.4 1768.62
    36.5 1768.79    40.5 1769.23    44.5 1769.94    48.5 1768.66    52.5 1765.89
    56.5 1764.27    60.5 1763.95    64.5 1763.81    68.5 1764.04    73.6 1764.12
    80.3 1763.61    85.4 1763.25    88.1 1763.87    93.8 1765.87    95.5 1766.14
    98.1  1766.5   102.5 1766.21   106.8 1766.43   111.2 1767.17   116.9 1769.07
   119.9 1769.92     123 1770.39   124.2 1770.53   128.6 1770.55   140.3 1770.36
#Mann= 3 ,-1,0
       0      .1       0    80.3    .045       0    88.1      .1       0
Bank Sta=80.3,88.1
XS Rating Curve= 0 ,0
Exp/Cntr(USF)=0,0
Exp/Cntr=0.3,0.1

Type RM Length L Ch R = 1 ,1586    ,55.2,54.7,52.2
XS GIS Cut Line= 5
2194711.22586063677997.2756677492194745.49970818678002.171931684
2194770.54598138678003.3018387472194810.09272855677995.580807156
2194829.86610214677985.599961442
#Sta/Elev= 30
       0 1768.27       5 1768.43       9 1767.33    13.1 1766.69    17.1 1766.48
    21.2 1765.88    29.2 1763.84    36.2 1762.81    41.3  1762.3    45.3 1762.29
    49.3 1763.11    53.3 1763.78    57.3 1764.15    61.4 1764.21    65.4 1763.46
    72.61760.633    73.6 1760.25    76.5 1759.85    77.7 1759.72    81.7  1759.6
    85.8 1759.88    87.41760.085    90.2 1760.48      94 1761.34      97 1762.34
      98 1762.79     100 1763.47   102.3 1764.37   105.3 1765.17   122.1 1768.27
#Mann= 3 ,-1,0
       0      .1       0    72.6    .045       0    87.4      .1       0
Bank Sta=72.6,87.4
XS Rating Curve= 0 ,0
Exp/Cntr(USF)=0,0
Exp/Cntr=0.3,0.1

Type RM Length L Ch R = 1 ,1531    ,89.2,99,108
XS GIS Cut Line= 4
2194747.55885499678062.0318925332194794.95037071678052.220507045
2194819.62749961678044.1866456762194852.53481576678027.194641396
#Sta/Elev= 30
       0 1762.11     4.7  1761.5     8.8  1760.6    12.9 1759.21    24.9 1754.53
    29.2  1753.2    33.3 1752.49    37.4 1752.12    45.6 1752.32    49.7  1751.5
    52.61750.592    53.9 1750.19      55 1750.02    58.1 1749.74    61.3 1750.18
    62.3 1750.42    64.5 1751.04    66.5  1751.7    70.5 1753.11      75 1754.83
      77 1755.93      80 1757.36    82.9 1758.63      84 1759.04    89.6 1762.05
      93  1763.6    94.8 1764.04    97.5 1764.52   106.7 1764.45   111.4  1764.5
#Mann= 4 ,-1,0
       0     .06       0    52.6    .045       0    62.3     .06       0
   84.35      .1       0
Bank Sta=52.6,62.3
XS Rating Curve= 0 ,0
Exp/Cntr(USF)=0,0
Exp/Cntr=0.3,0.1

Type RM Length L Ch R = 1 ,1432    ,71.2,65.3,59
XS GIS Cut Line= 4
2194734.39360937678104.7419923532194765.39243137 678123.68571691
2194804.71501113678144.9256505052194855.51863608678142.342415338
#Sta/Elev= 30
       0  1759.8     6.8 1759.88    13.3 1759.45    16.2 1759.18    20.8 1758.32
      22  1757.9    27.8 1755.59    30.7  1754.2    33.6 1752.11    39.5 1746.87
      44 1744.11    48.6 1743.46    50.81743.561    54.2 1743.61    57.2 1744.06
    60.1 1744.37    66.1 1745.54    73.1 1748.15    75.9 1748.88    80.4 1749.63
    84.5 1749.78    92.5 1749.62    96.5  1749.8   100.5 1750.82   104.5  1752.4
   112.5 1757.05   116.5 1758.56   120.5 1758.76   124.5 1758.39   131.9 1758.23
#Mann= 5 ,-1,0
       0     .06       0      44     .06       0    50.8    .045       0
    57.2     .06       0  101.02      .1       0
Bank Sta=44,57.2
XS Rating Curve= 0 ,0
Exp/Cntr(USF)=0,0
Exp/Cntr=0.3,0.1

Type RM Length L Ch R = 1 ,1367    ,101.5,110.9,116.1
XS GIS Cut Line= 4
2194707.57548634678185.6873375462194747.35730791678197.570219314
2194784.03924728 678195.503631182194852.75330272678182.845778863
#Sta/Elev= 30
       0 1755.27    12.2 1753.95    17.3 1753.03    25.7 1750.24    29.8 1748.99
      34  1748.1    38.2 1746.85    42.7  1744.7    50.4 1740.49    54.4 1740.14
      571740.094    58.4 1740.06    66.4  1740.1    68.71740.577    70.4 1740.93
    74.4 1742.48    78.4 1743.61    82.5 1744.29    86.5 1745.21    94.1 1746.33
   102.8 1747.79   106.9 1748.09   110.9 1748.11   119.1 1748.72   127.2 1750.09
   131.3 1751.02   139.4 1752.48   145.6 1755.02   147.5 1755.71   148.1  1755.8
#Mann= 6 ,-1,0
       0      .1       0      20     .06       0    50.4     .06       0
      57    .045       0    68.7     .06       0  118.26      .1       0
Bank Sta=50.4,68.7
XS Rating Curve= 0 ,0
Exp/Cntr(USF)=0,0
Exp/Cntr=0.3,0.1

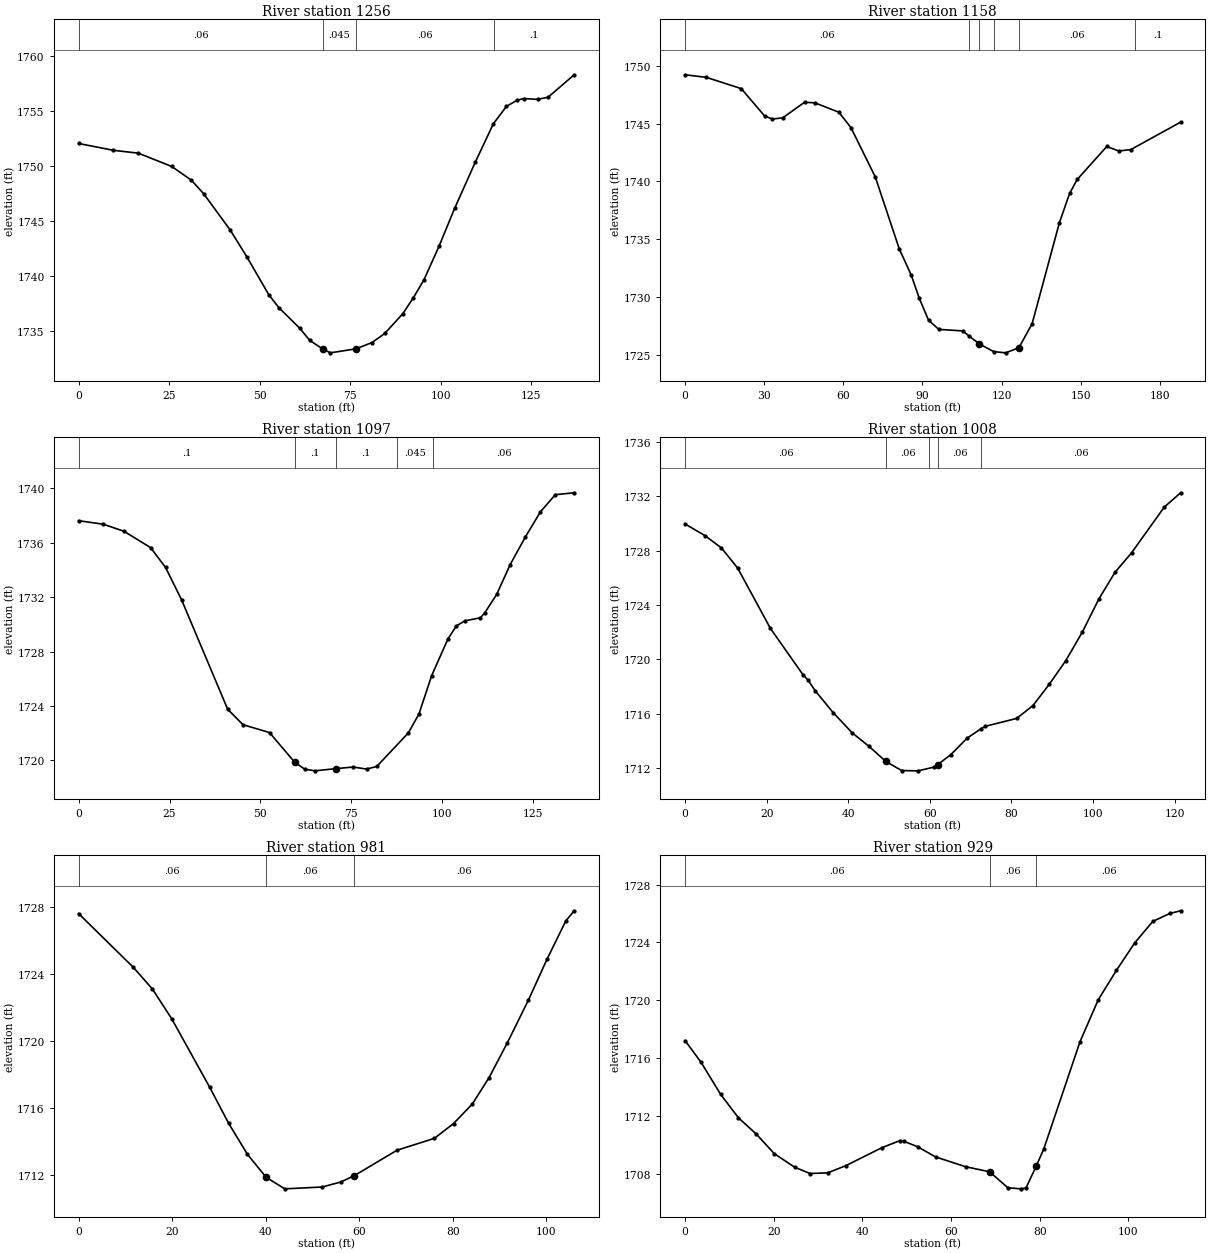
Type RM Length L Ch R = 1 ,1256    ,95,97.8,99.7
XS GIS Cut Line= 3
2194701.18661785678234.021263274 2194744.2405373678282.177869471
2194801.96468115678325.550706841
#Sta/Elev= 30
       0 1752.04     9.6 1751.42    16.5 1751.16    25.7 1749.95    31.1 1748.71
    34.5 1747.48    41.8 1744.19    46.5  1741.7    52.5 1738.28    55.3  1737.1
      61 1735.25    63.8 1734.13    67.41733.352    69.5    1733    76.61733.365
      81 1733.94    84.5 1734.76    89.5 1736.56    92.4 1738.01    95.3 1739.62
    99.5  1742.7   103.8 1746.14   109.5 1750.34   114.5 1753.84   118.1 1755.41
     121 1755.97   122.9 1756.13   126.7 1756.05   129.6 1756.25   136.8 1758.29
#Mann= 4 ,-1,0
       0     .06       0    67.4    .045       0    76.6     .06       0
   114.6      .1       0
Bank Sta=67.4,76.6
XS Rating Curve= 0 ,0
Exp/Cntr(USF)=0,0
Exp/Cntr=0.3,0.1

Type RM Length L Ch R = 1 ,1158    ,61.8,61,59.1
XS GIS Cut Line= 4
2194630.21972353678262.1469653152194670.46725276678334.767507187
2194712.02720142678388.1392307322194744.83768721678405.638156484
#Sta/Elev= 30
       0 1749.24       8 1749.02    21.3 1748.04    30.2 1745.66    33.1 1745.41
      37 1745.51    45.3 1746.86    49.2 1746.81    58.3    1746    62.9 1744.66
    72.1  1740.4    81.2 1734.17    85.8 1731.86    88.8 1729.88    92.3 1727.99
    96.2 1727.19   105.3 1727.06   107.7 1726.61   111.6 1725.93     1171725.266
   121.6 1725.16   126.6 1725.61   131.6 1727.69   141.9 1736.41   145.8 1738.96
   148.7 1740.18   159.9 1743.03   164.4 1742.64     169 1742.76   187.9 1745.14
#Mann= 6 ,-1,0
       0     .06       0   107.7    .045       0   111.6    .045       0
     117     .06       0   126.6     .06       0  170.67      .1       0
Bank Sta=111.6,126.6
XS Rating Curve= 0 ,0
Exp/Cntr(USF)=0,0
Exp/Cntr=0.3,0.1

Type RM Length L Ch R = 1 ,1097    ,95.8,89.4,82.8
XS GIS Cut Line= 5
 2194592.9949663678344.3900477212194615.47909401678366.658880862
 2194654.4459974678404.462593108 2194674.2145843678415.417584087
2194701.33536629678421.539655173
#Sta/Elev= 30
       0 1737.61     6.8 1737.35    12.5 1736.83    19.8 1735.63    23.9 1734.18
    28.3 1731.81      41 1723.76    45.2 1722.63    52.5 1722.05    59.4 1719.88
    62.2 1719.36      65 1719.24    70.7  1719.4    75.5 1719.52    79.2 1719.37
      82 1719.56    90.7 1722.03    93.6 1723.41    97.1 1726.23   101.6 1728.94
   103.9 1729.88   106.2 1730.25   110.5 1730.48   111.7 1730.84     115  1732.2
   118.7 1734.39   122.8 1736.38     127 1738.25   131.1 1739.52   136.3 1739.66
#Mann= 5 ,-1,0
       0      .1       0    59.4      .1       0    70.7      .1       0
    87.5    .045       0    97.4     .06       0
Bank Sta=59.4,70.7
XS Rating Curve= 0 ,0
Exp/Cntr(USF)=0,0
Exp/Cntr=0.3,0.1

Type RM Length L Ch R = 1 ,1008    ,28.7,26.2,25.6
XS GIS Cut Line= 3
2194563.33552359678465.6118833782194604.93301789 678468.96429198
2194684.15222967678478.436154258
#Sta/Elev= 30
       0 1729.97     4.9 1729.11     8.9 1728.21    12.9 1726.72    20.9 1722.29
    28.9 1718.87    30.1 1718.49    31.9 1717.69    36.3 1716.08      41 1714.58
      45 1713.62    49.21712.485    53.1 1711.81    57.1 1711.79    61.1 1712.07
    61.91712.239    65.1 1712.97    69.2 1714.21    72.6  1714.9    73.6 1715.07
    81.3 1715.65    85.3  1716.6    89.3 1718.17    93.3 1719.89    97.4 1722.01
   101.4 1724.42   105.4 1726.41   109.5 1727.86   117.5 1731.22   121.5 1732.27
#Mann= 5 ,-1,0
       0     .06       0    49.2     .06       0    59.9    .045       0
    61.9     .06       0    72.6     .06       0
Bank Sta=49.2,61.9
XS Rating Curve= 0 ,0
Exp/Cntr(USF)=0,0
Exp/Cntr=0.3,0.1

Type RM Length L Ch R = 1 ,981     ,58.3,51.9,46.1
XS GIS Cut Line= 4
2194560.75982581678488.4497369772194591.32477273678494.974838005
2194621.54629329678496.1768302992194666.02000819678498.409101704
#Sta/Elev= 22
       0 1727.59    11.7 1724.39    15.8 1723.09    19.9 1721.33      28 1717.26
    32.1 1715.09    36.1 1713.25    40.1 1711.88    44.1 1711.19    52.1  1711.3
    56.1  1711.6      59 1711.98    68.1 1713.49    76.1  1714.2    80.2 1715.08
    84.2 1716.24    87.8 1717.82    91.7 1719.89    96.2 1722.43   100.2 1724.88
   104.2 1727.15     106 1727.76
#Mann= 3 ,-1,0
       0     .06       0    40.1     .06       0      59     .06       0
Bank Sta=40.1,59
XS Rating Curve= 0 ,0
Exp/Cntr(USF)=0,0
Exp/Cntr=0.3,0.1

Type RM Length L Ch R = 1 ,929     ,34.6,39.2,43
XS GIS Cut Line= 4
2194572.29380045678524.9739899822194635.38397201678534.487587281
 2194657.9494885 678529.832614552194682.33276076678524.681219002
#Sta/Elev= 29
       0  1717.2     3.6  1715.7       8 1713.49      12 1711.87    16.1 1710.72
    20.1 1709.38    24.7 1708.44    28.2    1708    32.2 1708.05    36.3 1708.55
    44.4 1709.79    48.4 1710.27    49.3 1710.24    52.5 1709.85    56.5 1709.15
    63.3 1708.47    68.7 1708.12    72.8 1707.02    75.7 1706.94    76.9 1706.99
    79.2  1708.5    80.9 1709.68    89.1 1717.13    93.2 1720.02    97.3 1722.06
   101.4 1723.95   105.5 1725.45   109.4 1726.01   111.8 1726.19
#Mann= 3 ,-1,0
       0     .06       0    68.7     .06       0    79.2     .06       0
Bank Sta=68.7,79.2
XS Rating Curve= 0 ,0
Exp/Cntr(USF)=0,0
Exp/Cntr=0.3,0.1