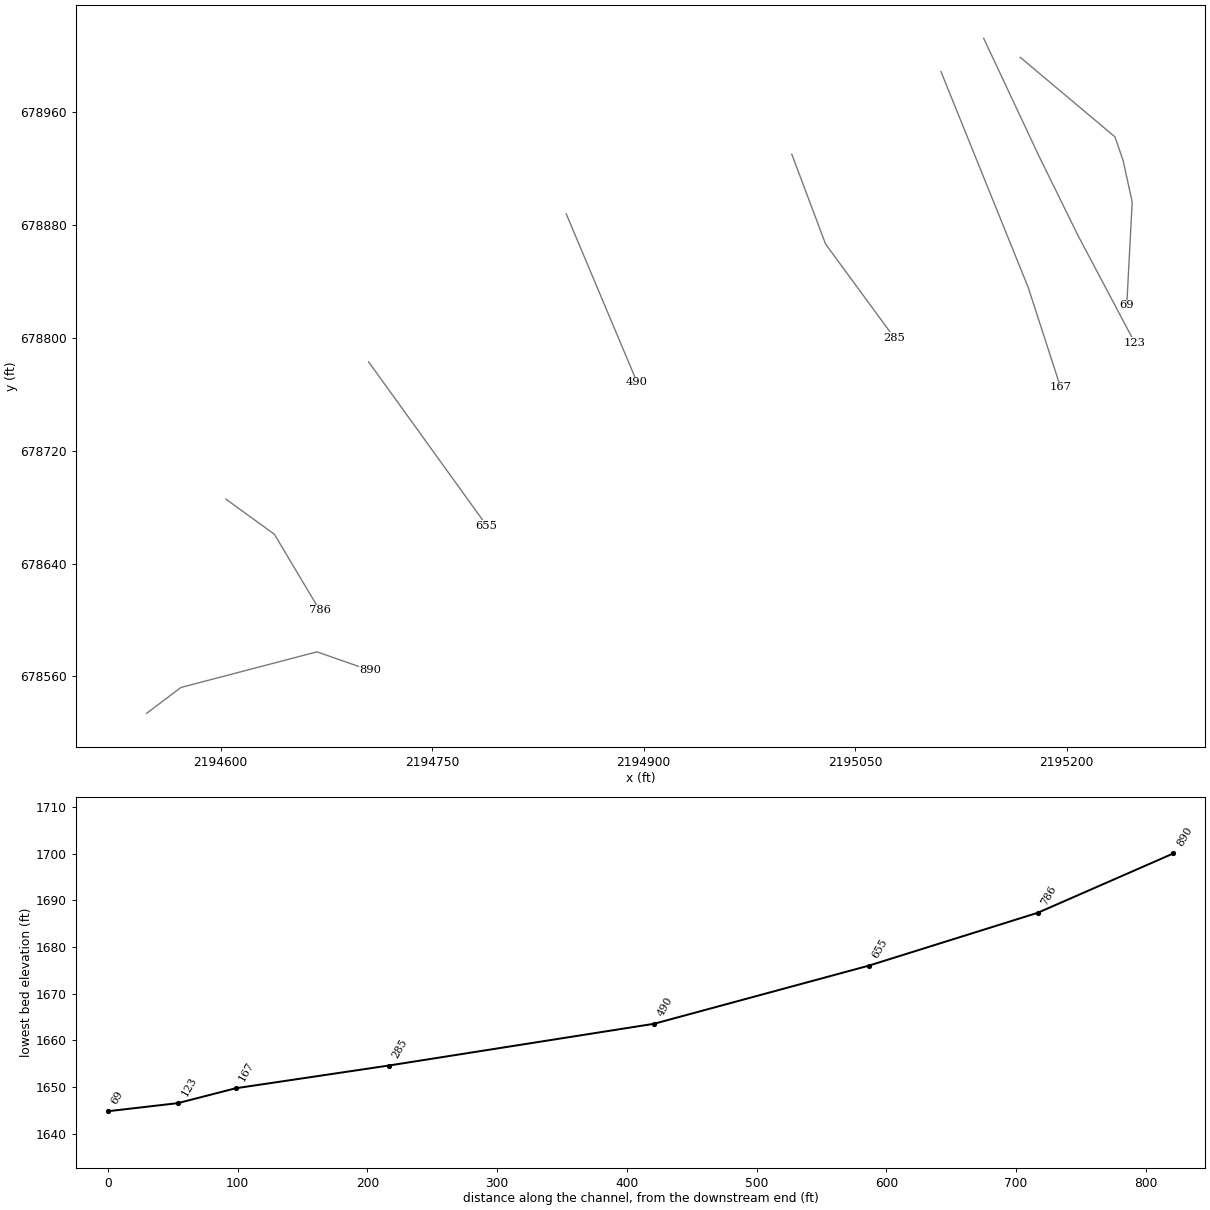
HEC-RAS study INDIANCPRN.prj: INDIANCPRN

--- INDIANCPRN.g01 (geometry) --- (continued)

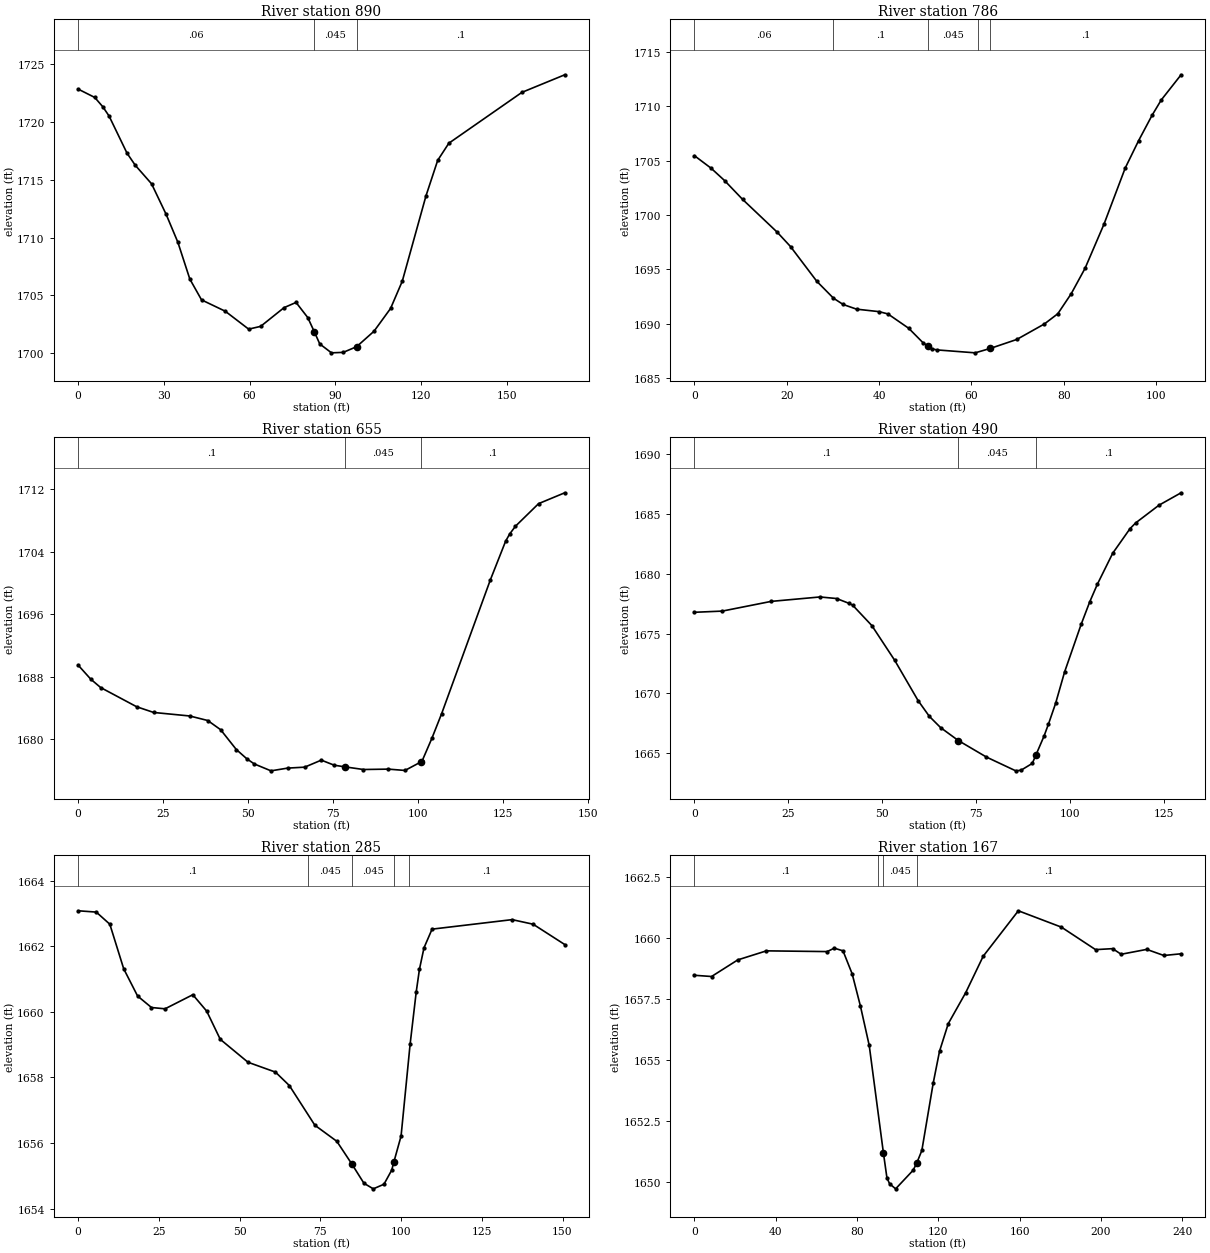
Type RM Length L Ch R = 1 ,890     ,114.9,104.6,81.5
XS GIS Cut Line= 4
2194547.52779196678533.8321972812194571.92501298678552.201869579
2194668.36579254678577.4601689882194706.25324166678564.256967024
#Sta/Elev= 30
       0 1722.85     5.8 1722.13     8.6 1721.33    10.8 1720.53    17.1 1717.31
      20 1716.26    25.7 1714.66    30.8 1712.02    34.9 1709.61    39.1 1706.42
    43.2 1704.62    51.5 1703.64    59.7 1702.09    63.9 1702.33    72.1 1703.95
    76.3  1704.4    80.4 1703.09    82.71701.857    84.6 1700.81    88.7 1700.04
    92.8 1700.08    97.5 1700.57   103.6 1701.91   109.4 1703.88   113.5 1706.24
   121.8 1713.62   125.9 1716.69   129.8 1718.17   155.4 1722.57   170.4 1724.09
#Mann= 3 ,-1,0
       0     .06       0    82.7    .045       0    97.5      .1       0
Bank Sta=82.7,97.5
XS Rating Curve= 0 ,0
Exp/Cntr(USF)=0,0
Exp/Cntr=0.3,0.1

Type RM Length L Ch R = 1 ,786     ,127,130.4,130.4
XS GIS Cut Line= 3
2194603.77987859678685.7999040292194638.22301415 678660.82863075
2194670.36994067678606.867718376
#Sta/Elev= 30
       0 1705.46     3.6 1704.31     6.5 1703.18    10.4 1701.45    17.9 1698.43
    20.8  1697.1    26.5  1693.9    30.1 1692.35    32.2 1691.77    35.1 1691.34
      40 1691.11    41.9  1690.9    46.4 1689.58    49.5 1688.25    50.51687.955
    51.4 1687.69    52.5 1687.59    60.8 1687.32    64.1 1687.73    69.8 1688.55
    75.8 1689.98    78.7 1690.92    81.6 1692.76    84.6  1695.1    88.7 1699.16
    93.3 1704.33    96.2 1706.85    99.1 1709.17   101.1 1710.59   105.4 1712.91
#Mann= 5 ,-1,0
       0     .06       0      30      .1       0    50.5    .045       0
    61.5      .1       0    64.1      .1       0
Bank Sta=50.5,64.1
XS Rating Curve= 0 ,0
Exp/Cntr(USF)=0,0
Exp/Cntr=0.3,0.1

Type RM Length L Ch R = 1 ,655     ,166,165.4,161.7
XS GIS Cut Line= 2
2194704.97914048678783.1653921062194788.69313714678667.045977393
#Sta/Elev= 30
       0  1689.5     3.7 1687.71     6.6 1686.64    17.2 1684.18    22.2 1683.45
    32.8    1683    38.1 1682.42    41.9 1681.24    46.5 1678.71    49.6 1677.52
    51.8 1676.86    56.7 1675.98    61.6 1676.33    66.6 1676.45    71.5 1677.35
    75.3  1676.7    78.41676.492    83.9 1676.15    91.2  1676.2    96.1 1676.03
   100.81677.119   101.1  1677.2     104 1680.12   106.9 1683.31   121.2  1700.4
   125.7 1705.36   126.9 1706.29   128.6 1707.28   135.4 1710.17   143.1 1711.56
#Mann= 3 ,-1,0
       0      .1       0    78.4    .045       0   100.8      .1       0
Bank Sta=78.4,100.8
XS Rating Curve= 0 ,0
Exp/Cntr(USF)=0,0
Exp/Cntr=0.3,0.1

Type RM Length L Ch R = 1 ,490     ,199.4,204.4,205
XS GIS Cut Line= 2
 2194845.1899906 678887.997734482194895.41838859678768.637777961
#Sta/Elev= 30
       0 1676.78     7.4 1676.88    20.4 1677.69    33.4 1678.06    37.8 1677.93
    41.1 1677.53    42.1 1677.37    47.2 1675.67    53.3 1672.76    59.5 1669.41
    62.5 1668.09    65.5 1667.15    70.21666.073    77.7 1664.69    85.5 1663.54
    86.9 1663.59    89.9 1664.16    90.91664.889      93 1666.42    94.2 1667.44
    96.1 1669.17    98.5  1671.8   102.9 1675.77   105.2 1677.66   107.2 1679.11
   111.3 1681.71   115.9 1683.76   117.4 1684.24   123.6 1685.72   129.5 1686.76
#Mann= 3 ,-1,0
       0      .1       0    70.2    .045       0    90.9      .1       0
Bank Sta=70.2,90.9
XS Rating Curve= 0 ,0
Exp/Cntr(USF)=0,0
Exp/Cntr=0.3,0.1

Type RM Length L Ch R = 1 ,285     ,120.5,118,115
XS GIS Cut Line= 3
 2195005.1010071678930.3926627472195029.11828269 678866.60907838
2195077.94028554678800.069413207
#Sta/Elev= 30
       0 1663.08     5.6 1663.04     9.8 1662.67    14.1 1661.31    18.4 1660.48
    22.7 1660.13    26.9 1660.09    35.5 1660.52    39.8 1660.02      44 1659.16
    52.6 1658.46    61.1 1658.16    65.4 1657.75    73.3 1656.54    80.1 1656.05
    84.8 1655.35    88.5 1654.77    91.4  1654.6    94.7 1654.74    97.1 1655.17
    97.8 1655.43     100 1656.21   102.8 1659.01   104.7 1660.61   105.7  1661.3
   107.1 1661.95   109.6 1662.52   134.4 1662.81   140.9 1662.67   150.7 1662.05
#Mann= 5 ,-1,0
       0      .1       0    71.3    .045       0    84.8    .045       0
    97.8      .1       0   102.5      .1       0
Bank Sta=84.8,97.8
XS Rating Curve= 0 ,0
Exp/Cntr(USF)=0,0
Exp/Cntr=0.3,0.1

Type RM Length L Ch R = 1 ,167     ,43.1,44.6,46.2
XS GIS Cut Line= 3
2195110.91977183678988.9507940992195172.78984866678835.870191619
2195195.75193903678765.070412972
#Sta/Elev= 30
       0 1658.47     8.4 1658.42    21.3  1659.1    35.4 1659.47    65.3 1659.44
    68.8 1659.58    73.1 1659.47    77.6 1658.53    81.7  1657.2      86  1655.6
      93 1651.19    94.7 1650.19      96 1649.94      99 1649.73   107.6 1650.49
   109.41650.786   111.9  1651.3   117.5 1654.06   120.6 1655.36   124.9 1656.49
   133.5 1657.76   142.1 1659.25   159.4 1661.11   180.6 1660.44   197.4 1659.52
   205.8 1659.56     210 1659.33   222.6 1659.53     231 1659.28   239.5 1659.35
#Mann= 4 ,-1,0
       0      .1       0    90.2    .045       0      93    .045       0
   109.4      .1       0
Bank Sta=93,109.4
XS Rating Curve= 0 ,0
Exp/Cntr(USF)=0,0
Exp/Cntr=0.3,0.1

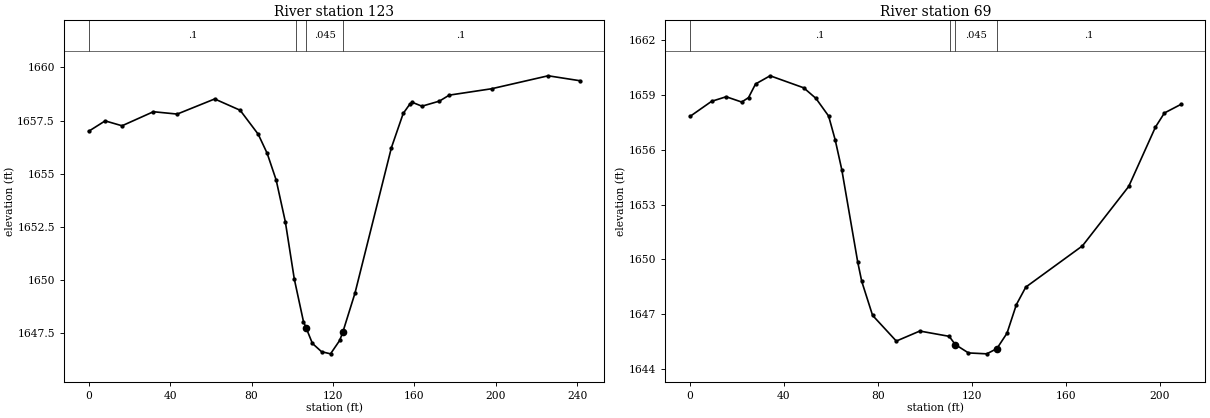
Type RM Length L Ch R = 1 ,123     ,56.5,53.9,49.4
XS GIS Cut Line= 4
 2195141.2169744679012.5507203142195180.12496086678929.632060638
2195208.18973799 678872.545752632195248.37339614678796.643287234
#Sta/Elev= 30
       0    1657     8.1 1657.49    16.4 1657.26    31.8 1657.92    43.5 1657.81
    61.9 1658.52    74.4 1657.99    83.3 1656.86    87.7 1655.96    92.1 1654.71
    96.6 1652.75     101 1650.06   105.5 1648.06   106.9 1647.74   109.9 1647.03
   114.4 1646.64   118.8 1646.54   123.3 1647.17   124.8 1647.55   130.8 1649.39
   148.7 1656.23   154.5 1657.84   157.7 1658.27     159 1658.36   163.7 1658.18
   172.3 1658.42   177.1  1658.7   197.9    1659   225.7 1659.61   241.1 1659.38
#Mann= 4 ,-1,0
       0      .1       0   101.9    .045       0   106.9    .045       0
   124.8      .1       0
Bank Sta=106.9,124.8
XS Rating Curve= 0 ,0
Exp/Cntr(USF)=0,0
Exp/Cntr=0.3,0.1

Type RM Length L Ch R = 1 ,69      ,,,
XS GIS Cut Line= 5
2195167.09788559678999.112274459 2195234.3099604678942.686169119
2195240.14293565678925.6733246382195246.53658468678896.417513614
2195242.66952019678823.313321426
#Sta/Elev= 30
       0 1657.83     9.2 1658.66    15.4 1658.91      22 1658.62    24.9 1658.86
    27.9 1659.61    34.1 1660.06    48.4  1659.4    53.6 1658.82      59 1657.85
    61.8 1656.54    64.6 1654.91    71.4 1649.83    73.1 1648.78    77.7 1646.92
    87.8 1645.51    97.8 1646.06   110.3 1645.77   112.9 1645.32   118.5 1644.86
   126.3 1644.81   130.61645.097   134.9 1645.94   138.9 1647.51   142.9 1648.47
     167 1650.73   186.7 1653.99   198.1 1657.25   201.9 1658.02   208.9 1658.49
#Mann= 4 ,-1,0
       0      .1       0   110.6    .045       0   112.9    .045       0
   130.6      .1       0
Bank Sta=112.9,130.6
XS Rating Curve= 0 ,0
Exp/Cntr(USF)=0,0
Exp/Cntr=0.3,0.1
LCMann Table=0

Chan Stop Cuts=-1
Use User Specified Reach Order=0
Composite Channel Slope=5